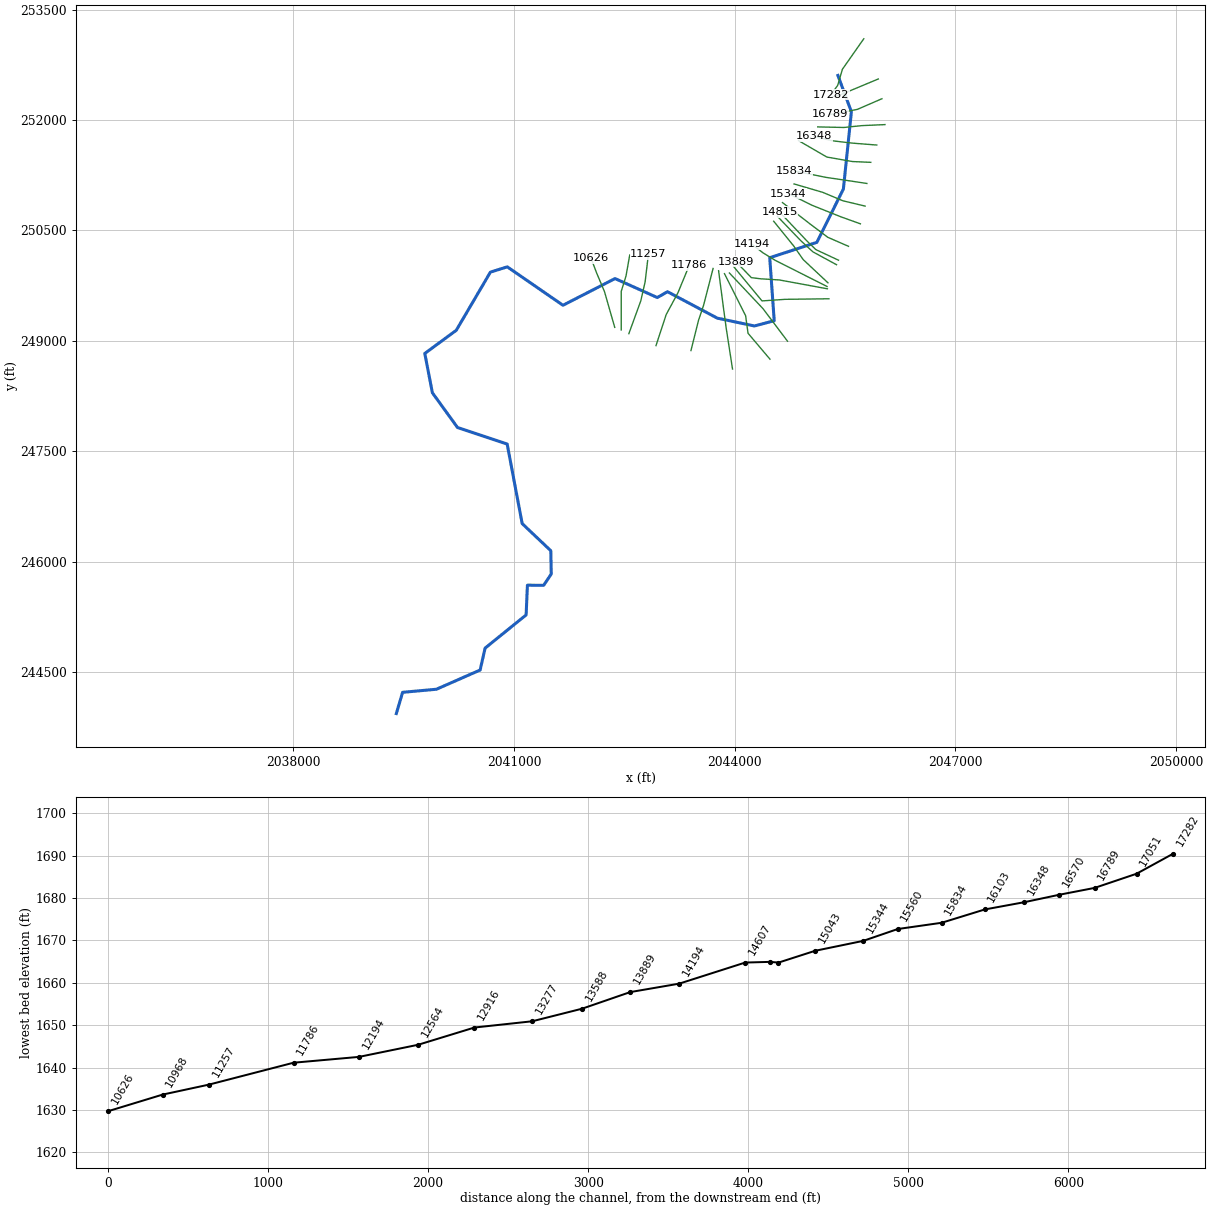
--- HNGRDCK_1.prj (project) ---

Proj Title=HNGRDCK_1
Current Plan=p01
Default Exp/Contr=0,0
English Units
Geom File=g01
Flow File=f01
Plan File=p01
BEGIN DESCRIPTION:
Stream Name: Hungard Creek
Flood Zone: Approximate
Summers County, West Virginia
HEC-RAS Version: 5.0.7
Hydrology Method:
Regression.
Model Notes:
END DESCRIPTION:
DSS File=dss
DSS Export Rating Curves= 0
DSS Export Rating Curve Sorted= 0
DSS Export Volume Flow Curves= 0
DXF Filename=HNGRDCK_A.
DXF OffsetX= 0
DXF OffsetY= 0
DXF ScaleX= 0
DXF ScaleY= 0

--- HNGRDCK_1.p01 (plan) ---

Plan Title=Floodplain
Program Version=5.07
Short Identifier=Floodplain
Geom File=g01
Flow File=f01
Subcritical Flow
K Sum by GR= 0
Std Step Tol= 0.01
Critical Tol= 0.01
Num of Std Step Trials= 20
Max Error Tol= 0.3
Flow Tol Ratio= 0.001
Split Flow NTrial= 30
Split Flow Tol= 0.02
Split Flow Ratio= 0.02
Log Output Level= 0
Friction Slope Method= 1
Unsteady Friction Slope Method= 2
Unsteady Bridges Friction Slope Method= 1
Parabolic Critical Depth
Global Vel Dist= 0 , 0 , 0
Global Log Level= 0
CheckData=True
Encroach Param=-1 ,0,0, 0
Computation Interval=0.1SEC
Output Interval=1MIN
Instantaneous Interval=Max Profile
Mapping Interval=1HOUR
Computation Time Step Use Courant=        0
Computation Time Step Use Time Series=    0
Computation Time Step Count To Double=0
Computation Time Step Max Doubling=0
Computation Time Step Max Halving=0
Computation Time Step Residence Courant=0
Run HTab= 0
Run UNet= 0
Run Sediment= 0
Run PostProcess= 0
Run WQNet= 0
Run RASMapper= 0
UNET Theta= 0
UNET Theta Warmup= 0
UNET ZTol= 0
UNET ZSATol= 0
UNET MxIter= 0
UNET Max Iter WO Improvement= 0
UNET MaxInSteps= 0
UNET DtIC= 0
UNET DtMin= 0
UNET MaxCRTS= 0
UNET WFStab= 0
UNET SFStab= 0
UNET WFX= 1
UNET SFX= 1
UNET 1D Methodology=Finite Difference
UNET DSS MLevel= 1
UNET Pardiso=0
UNET DZMax Abort= 0
UNET Use Existing IB Tables= 0
UNET Froude Reduction=False
UNET Froude Limit= 0
UNET Froude Power= 0
UNET D1 Cores= 0
UNET D2 Coriolis=0
UNET D2 Cores= 0
UNET D2 Theta= 1
UNET D2 Theta Warmup= 1
UNET D2 Z Tol= 0.01
UNET D2 Volume Tol= 0.01
UNET D2 Max Iterations= 20
UNET D2 Equation= 0
UNET D2 RampUpFraction=0.1
UNET D2 TimeSlices= 1
UNET D2 BCVolumeCheck=0
UNET D1D2 MaxIter= 0
UNET D1D2 ZTol=0.01
UNET D1D2 QTol=0.1
UNET D1D2 MinQTol=1
DSS File=dss
Write IC File= 0
Write IC File at Fixed DateTime=0
Write IC File at Sim End=0
Echo Input=False
Echo Parameters=False
Echo Output=False
Write Detailed= 0
HDF Write Warmup=0
HDF Write Time Slices=0
HDF Flush=0
HDF Face Node Velocities=0
HDF Compression= 1
HDF Chunk Size= 1
HDF Spatial Parts= 1
HDF Use Max Rows=0
HDF Fixed Rows= 1
Calibration Method= 0
Calibration Iterations= 20
Calibration Max Change=0.05
Calibration Tolerance=0.2
Calibration Maximum=1.5
Calibration Minimum=0.5
Calibration Optimization Method= 1
WQ AD Non Conservative
WQ ULTIMATE=-1
WQ Max Comp Step=1HOUR
WQ Output Interval=15MIN
WQ Output Selected Increments= 0
WQ Output face flow=0
WQ Output face velocity=0
WQ Output face area=0
WQ Output face dispersion=0
WQ Output cell volume=0
WQ Output cell surface area=0
WQ Output cell continuity=0
WQ Output cumulative cell continuity=0
WQ Output face conc=0
WQ Output face dconc_dx=0
WQ Output face courant=0
WQ Output face peclet=0
WQ Output face adv mass=0
WQ Output face disp mass=0
WQ Output cell mass=0
WQ Output cell source sink temp=0
WQ Output nsm pathways=0
WQ Output nsm derived pathways=0
WQ Output MaxMinRange=-1
WQ Daily Max Min Mean=-1
WQ Daily Range=0
WQ Daily Time=0
WQ Create Restart=0
WQ Fixed Restart=0
WQ System Summary=0
WQ Write To DSS=0
WQ Use Fixed Temperature=0
Sorting and Armoring Iterations= 10
XS Update Threshold= 0.02
Bed Roughness Predictor= 0
Hydraulics Update Threshold= 0.02
Energy Slope Method= 1
Volume Change Method= 1
Sediment Retention Method= 0
XS Weighting Method= 0
Number of US Weighted Cross Sections= 1
Number of DS Weighted Cross Sections= 1
Upstream XS Weight=0
Main XS Weight=1
Downstream XS Weight=0
Number of DS XS's Weighted with US Boundary= 1
Upstream Boundary Weight= 1
Weight of XSs Associated with US Boundary= 0
Number of US XS's Weighted with DS Boundary= 1
Downstream Boundary Weight= 0.5
Weight of XSs Associated with DS Boundary= 0.5
Percentile Method= 0
Sediment Output Level= 3
Mass or Volume Output= 0
Output Increment Type= 1
Profile and TS Output Increment= 1
XS Output Flag= 0
XS Output Increment= 10
Write Gradation File= 0
Read Gradation Hotstart= 0
Write HDF5 File= 1
Write Binary Output= 1
Write DSS Sediment File= 0
SV Curve= 0
Specific Gage Flag= 0

--- HNGRDCK_1.f01 (steady flow) ---

Flow Title=Flows
Program Version=5.07
Number of Profiles= 6
Profile Names=01pct,10pct,04pct,02pct,0_2pct,01plus
River Rch & RM=HNGRDCK_1,Main            ,17282
    2086    1159    1505    1786    2845    3086
River Rch & RM=HNGRDCK_1,Main            ,11257
    2344    1308    1694    2009    3189    3466
River Rch & RM=HNGRDCK_1,Main            ,2
    3054    1722    2219    2624    4134    4517
Boundary for River Rch & Prof#=HNGRDCK_1,Main            , 1
Up Type= 0
Dn Type= 1
Dn Known WS=1541.2
Boundary for River Rch & Prof#=HNGRDCK_1,Main            , 2
Up Type= 0
Dn Type= 1
Dn Known WS=1540.4
Boundary for River Rch & Prof#=HNGRDCK_1,Main            , 3
Up Type= 0
Dn Type= 1
Dn Known WS=1540.8
Boundary for River Rch & Prof#=HNGRDCK_1,Main            , 4
Up Type= 0
Dn Type= 1
Dn Known WS=1541
Boundary for River Rch & Prof#=HNGRDCK_1,Main            , 5
Up Type= 0
Dn Type= 1
Dn Known WS=1541.7
Boundary for River Rch & Prof#=HNGRDCK_1,Main            , 6
Up Type= 0
Dn Type= 1
Dn Known WS=1541.8
DSS Import GetInterval= 0
DSS Import GetPeak= 0
DSS Import FillOption= 0

--- HNGRDCK_1.g01 (geometry) ---

Geom Title=Geometry
Program Version=5.07

River Reach=HNGRDCK_1       ,Main
Reach XY= 30
2045402.17700002252605.4460000122045585.51900004252111.260999996
     2045476.789251062.4220000342045116.62300002250338.051000037
     2044475.815250128.868000011     2044536.697249272.988000028
     2044268.045249201.6020000212043763.46400004249307.865000037
2043086.38100002249667.023000036     2042947.492249587.813000015
     2042373.521249845.7420000162041665.71700003249482.921999993
2040908.98299999250004.8530000522040679.82700001249933.314000012
     2040215.417249142.5149999952039787.87600004 248828.25600001
2039890.88399999248293.9860000372040232.32299999247822.248999973
     2040907.257247597.3760000342041111.25000001246516.647000048
2041500.31300002246148.069999982     2041506.563245832.098000002
2041403.09100002245677.9319999632041182.62700001245679.883999975
2041164.89600001245275.847999998      2040607.49244825.057000022
     2040539.829244527.174000022     2039946.195244266.158000008
     2039486.424244224.4590000252039401.01026427243936.116604297

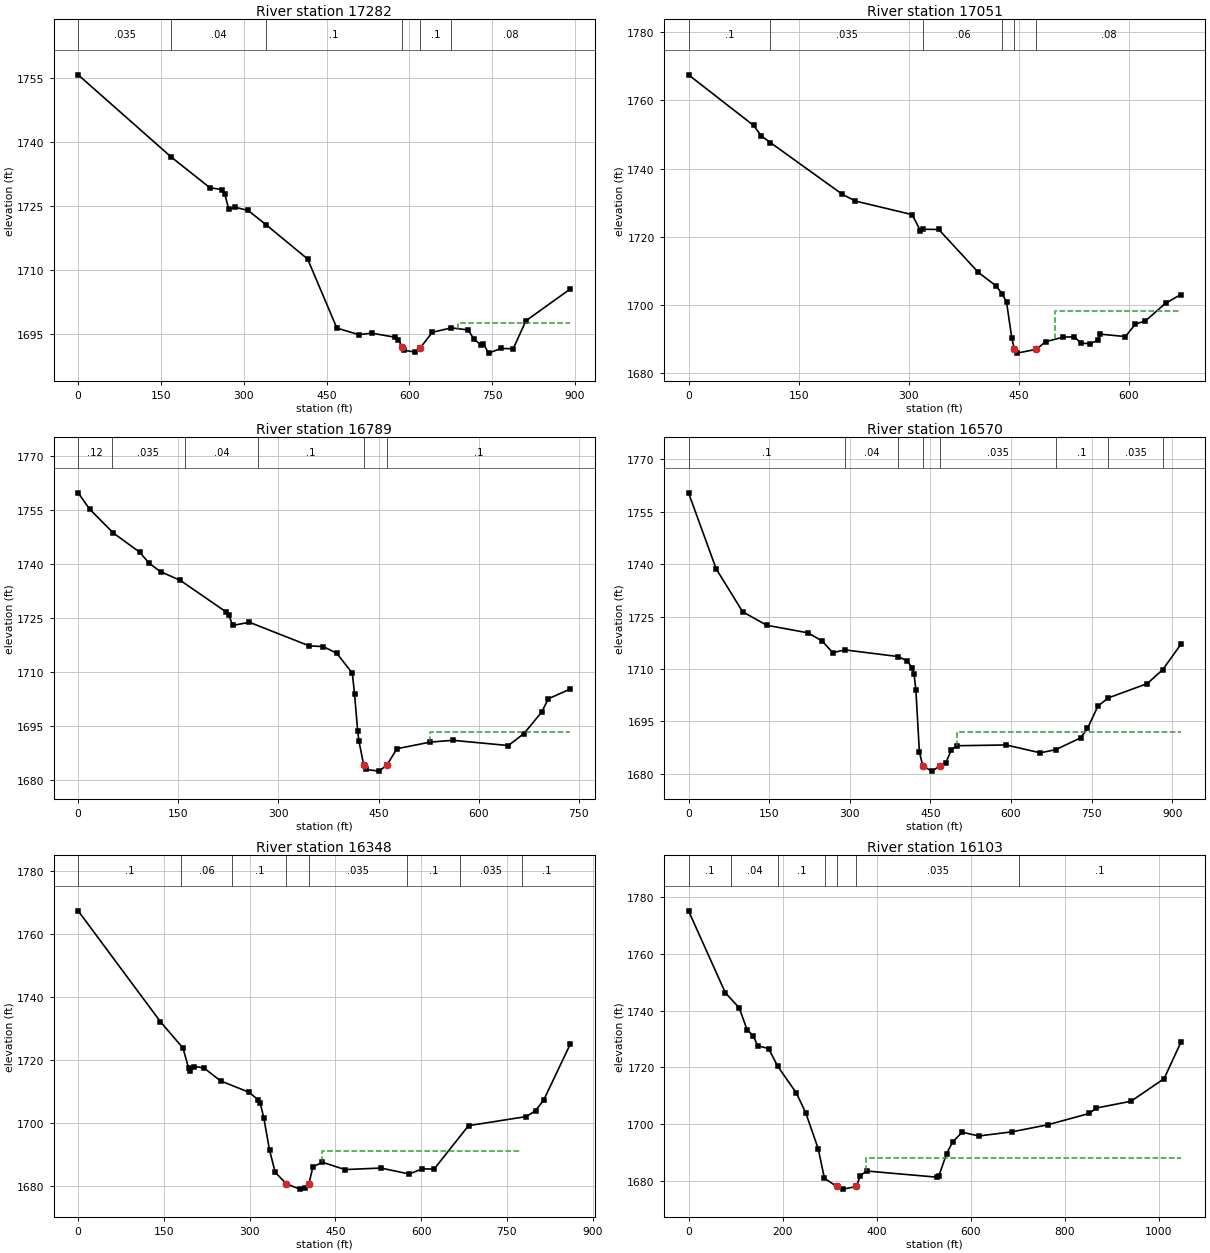
Type RM Length L Ch R = 1 ,17282   ,259,230.7,214.3
XS GIS Cut Line= 4
2045753.79288326253103.4690339342045463.35894855252689.116620413
2045399.46348291252470.323056264 2045306.5246238252342.532124991
#Sta/Elev= 30
       0 1755.83     169 1736.48   238.5 1729.33   261.3 1728.85   265.6 1727.87
   272.8 1724.26   284.4 1724.72     308 1723.98   340.9 1720.58   415.7 1712.58
   468.8 1696.35   508.5 1694.81   531.7 1695.16   573.4 1694.22   580.2 1693.67
   587.1 1691.86   590.5 1691.15     611  1690.7   619.5 1691.66   641.8 1695.36
     676  1696.4   706.7 1695.92   717.4 1693.68   730.6 1692.35   734.1 1692.73
   743.5 1690.47   766.5 1691.58   788.2 1691.47   811.2 1698.06891.9495 1705.56
#Mann= 6 ,-1 , 0
       0    .035       0     169     .04       0   340.9      .1       0
   587.1    .045       0   619.5      .1       0     676     .08       0
#XS Ineff= 2 , 0
                          687.68         1697.55
Permanent Ineff=
       F       F
Bank Sta=587.1,619.5
XS Rating Curve= 0 ,0
Exp/Cntr(USF)=0,0
Exp/Cntr=0.3,0.1

Type RM Length L Ch R = 1 ,17051   ,267.6,262.2,257.8
XS GIS Cut Line= 4
2045951.28795886252557.4532366772045622.12949952252419.981174247
2045436.25178131252342.5321249912045327.82311235252311.552505289
#Sta/Elev= 30
       0 1767.55    88.6 1752.68    99.3 1749.55   111.6 1747.62   209.5 1732.43
   227.3 1730.43   304.7 1726.44   316.1 1721.65     320 1722.13     341 1722.06
     395 1709.43   419.2 1705.46   427.7 1703.07   433.4 1700.63   440.6 1690.07
  444.031686.808   447.7  1685.7  473.671686.809   486.8 1689.06   510.5 1690.41
   525.5 1690.48   535.5 1688.59   547.2 1688.51   557.8 1689.45   561.3 1691.28
   595.3 1690.57     609 1694.24   622.7 1695.18     650 1700.36670.8476 1702.93
#Mann= 6 ,-1 , 0
       0      .1       0   111.6    .035       0     320     .06       0
   427.7     .08       0  444.03    .045       0  473.67     .08       0
#XS Ineff= 2 , 0
                             500            1698
Permanent Ineff=
       F       F
Bank Sta=444.03,473.67
XS Rating Curve= 0 ,0
Exp/Cntr(USF)=0,0
Exp/Cntr=0.3,0.1

Type RM Length L Ch R = 1 ,16789   ,221.8,219,216.6
XS GIS Cut Line= 4
 2045999.9764973252288.7880998632045667.48772884252144.500521099
2045469.87647967252105.2919399132045298.92706569252075.493418211
#Sta/Elev= 30
       0 1759.68      17 1755.19    52.8  1748.5    92.1  1743.2   106.4 1740.11
   123.4 1737.78   152.9 1735.37   220.9 1726.68   225.6 1725.74   231.6 1722.84
   256.6 1723.71   346.1 1717.17   367.2 1716.96   387.3 1715.11   410.7 1709.58
     414 1703.84   418.7 1693.58   420.7  1690.6  427.831684.039   430.7 1682.82
   450.8 1682.36   462.51684.039   477.6 1688.59   527.7 1690.43   561.2 1690.92
   644.4 1689.47   667.8 1692.79   694.4 1698.78   704.4 1702.47737.4373  1705.2
#Mann= 6 ,-1 , 0
       0     .12       0      50    .035       0     160     .04       0
     270      .1       0  427.83    .045       0   462.5      .1       0
#XS Ineff= 2 , 0
                          527.78         1693.33
Permanent Ineff=
       F       F
Bank Sta=427.83,462.5
XS Rating Curve= 0 ,0
Exp/Cntr(USF)=0,0
Exp/Cntr=0.3,0.1

Type RM Length L Ch R = 1 ,16570   ,228.5,221.7,218
XS GIS Cut Line= 4
2046042.32176498251937.479212437  2045725.516429 251923.36412321
2045483.99156889251898.2706312512045127.97765172251906.112347488
#Sta/Elev= 30
       0 1760.45    51.4 1738.69   100.7 1726.39   145.5 1722.53   222.2 1720.36
   248.5 1718.05   268.2 1714.69   291.2 1715.47   389.9 1713.57   406.5 1712.36
   416.4  1710.3   419.7 1708.53     423  1704.1   429.6 1686.28  435.921682.231
   452.7 1680.76   467.8 1682.23   479.1 1683.21     489 1686.87   498.9 1688.03
   591.1 1688.25   654.4    1686     683 1686.89   729.5 1690.27   742.4 1692.98
   761.7 1699.35   780.9 1701.71   853.6 1705.82   882.6 1709.85916.0448 1717.04
#Mann= 8 ,-1 , 0
       0      .1       0   291.2     .04       0   389.9    .035       0
  435.92    .045       0   467.8    .035       0     683      .1       0
   780.9    .035       0   882.6      .1       0
#XS Ineff= 2 , 0
                             500        1691.952
Permanent Ineff=
       F       F
Bank Sta=435.92,467.8
XS Rating Curve= 0 ,0
Exp/Cntr(USF)=0,0
Exp/Cntr=0.3,0.1

Type RM Length L Ch R = 1 ,16348   ,246.5,244.9,242.8
XS GIS Cut Line= 4
2045930.96939441 251659.882457642045606.32234219251684.975949599
2045336.56730363251716.3428145472045079.35901105 251775.93985795
#Sta/Elev= 30
       0 1767.39   143.9 1732.17   183.4 1723.78   193.2 1717.44   196.5 1716.41
   203.1 1717.92   219.6 1717.54   249.2 1713.36   298.5 1709.78     315 1707.37
   318.3 1706.46   324.9  1701.5   334.8 1691.37   344.7 1684.32  364.281680.667
   387.6 1678.98   397.5 1679.23  403.671680.667   410.7 1686.07   427.3 1687.51
   466.9 1685.19   529.6 1685.68   579.2 1683.78   602.4 1685.46   622.6 1685.32
   682.9 1699.14   784.3 1702.04   800.4 1703.94   814.6 1707.34861.2105 1725.15
#Mann= 8 ,-1 , 0
       0      .1       0     180     .06       0     270      .1       0
  364.28    .045       0  403.67    .035       0  575.62      .1       0
  667.19    .035       0  777.19      .1       0
#XS Ineff= 1 ,-1
  426.89  772.161691.079
Permanent Ineff=
       T
Bank Sta=364.28,403.67
XS Rating Curve= 0 ,0
Exp/Cntr(USF)=0,0
Exp/Cntr=0.3,0.1

Type RM Length L Ch R = 1 ,16103   ,268.5,269.5,270.4
XS GIS Cut Line= 4
2045849.41554555251424.630970524 2045600.0489692251435.609373256
2045251.87676827251496.7747599062044867.63267265251719.479501042
#Sta/Elev= 30
       0 1775.02    78.4 1746.22   107.9 1740.93   124.4 1733.29   137.5 1731.15
   147.3 1727.62   170.3 1726.65     190 1720.36   229.4 1711.04   249.1 1704.17
   275.8 1691.52   289.1  1681.1  315.141678.222   329.1 1677.28  357.041678.223
   365.7 1682.05   379.1 1683.64     529 1681.47   532.3 1681.76   548.9 1689.72
   562.3 1693.96   582.3 1697.26   617.3 1695.95   688.2  1697.4     765 1699.91
   852.4 1703.86   867.6 1705.76   941.4 1708.15  1011.7 1716.08 1047.23 1728.79
#Mann= 7 ,-1 , 0
       0      .1       0      90     .04       0     190      .1       0
  289.61    .035       0  315.14    .045       0  357.04    .035       0
  703.11      .1       0
#XS Ineff= 2 , 0
                          378.36          1688.1
Permanent Ineff=
       F       F
Bank Sta=315.14,357.04
XS Rating Curve= 0 ,0
Exp/Cntr(USF)=0,0
Exp/Cntr=0.3,0.1

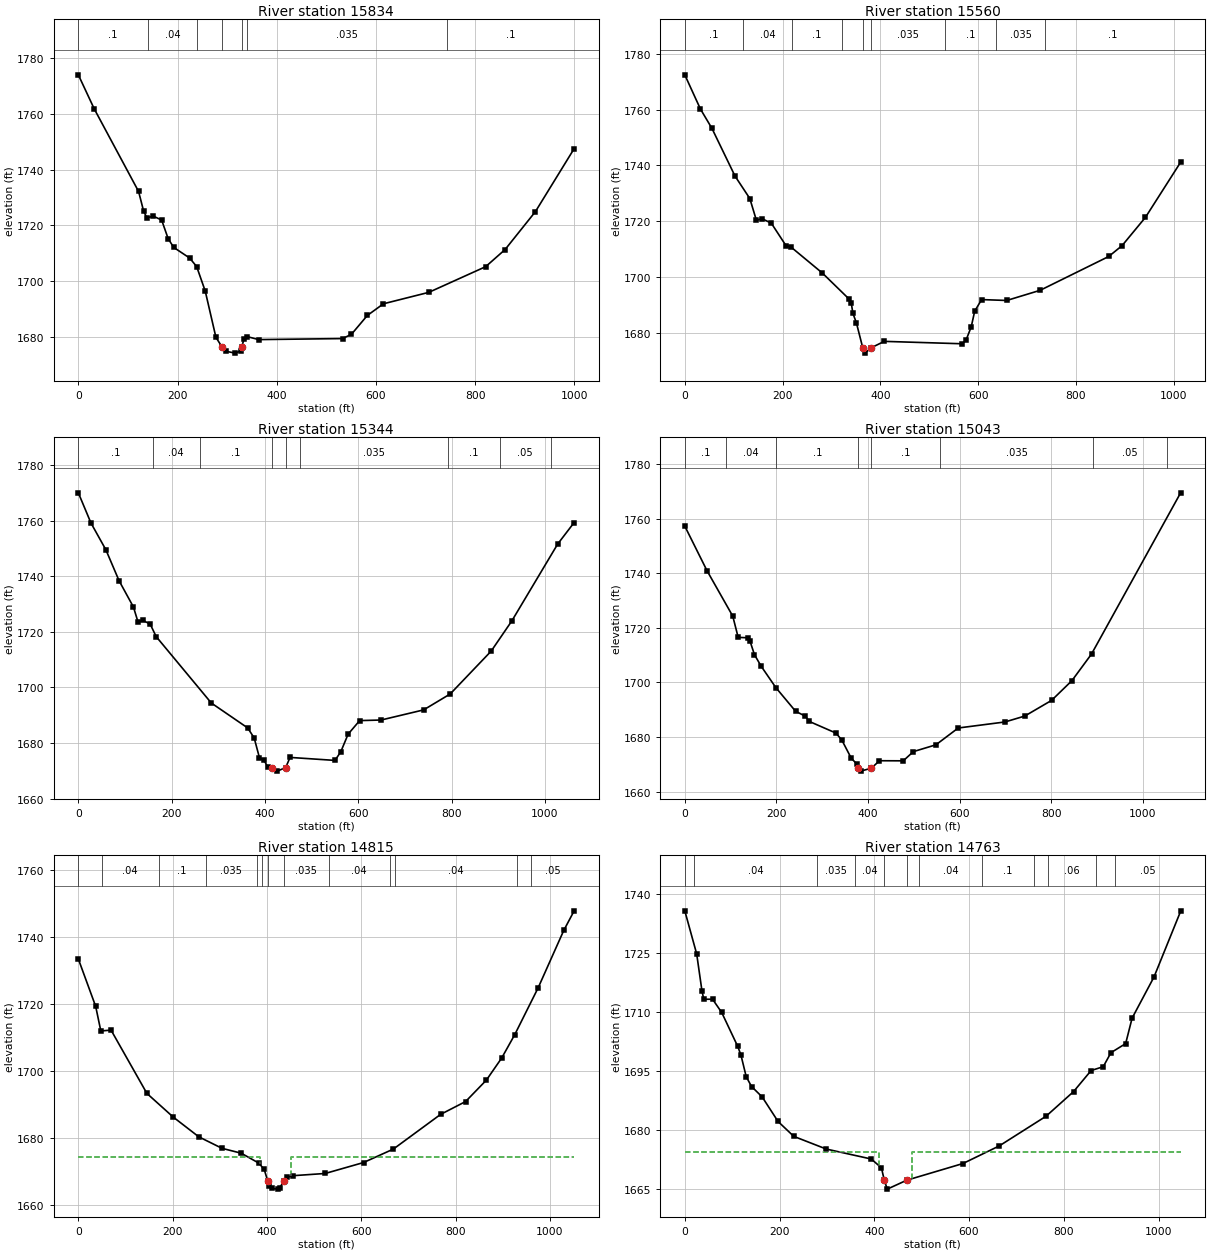
Type RM Length L Ch R = 1 ,15834   ,279.6,273.9,267.6
XS GIS Cut Line= 4
2045796.09187513251137.6241562422045568.68210425251172.127707686
2045239.33002229251220.7463483562044811.17231574251307.005226966
#Sta/Elev= 30
       0 1774.11    31.9 1761.94   121.5  1732.2   131.5 1725.24   138.1 1722.73
   151.4 1723.32     168 1721.94   181.2 1715.21   192.4 1712.11   224.4  1708.3
   238.6 1705.23   255.9  1696.4   277.4 1679.82  289.811676.328   297.3 1674.81
   316.6 1674.14   327.2 1674.97  329.42 1676.33   333.8  1679.1   340.4 1680.07
   363.7    1679   532.8 1679.37   550.7 1680.91   582.7 1687.67   615.2 1691.87
   706.6 1695.97   821.3  1705.2   860.5 1711.36   921.6 1724.98 999.694  1747.6
#Mann= 7 ,-1 , 0
       0      .1       0     140     .04       0  240.01      .1       0
  289.81    .045       0  329.42      .1       0  340.01    .035       0
  742.93      .1       0
Bank Sta=289.81,329.42
XS Rating Curve= 0 ,0
Exp/Cntr(USF)=0,0
Exp/Cntr=0.3,0.1

Type RM Length L Ch R = 1 ,15560   ,213.8,216,217.6
XS GIS Cut Line= 4
2045772.56672642250830.2288797442045469.87647967250902.372669126
2045196.98475461251016.861726189  2044806.467286251131.350783252
#Sta/Elev= 30
       0 1772.51    31.9 1760.26    55.5  1753.3   102.7 1736.19     133 1728.13
   146.5 1720.27   157.5 1720.93   176.9  1719.3   207.2 1711.16   217.4  1710.7
   281.4 1701.39   336.4    1692   340.3 1690.79   343.8 1686.96     351  1683.5
  363.921674.595   368.7 1672.67  381.331674.596   407.9 1676.89     567 1676.03
   575.1 1677.29   585.8  1682.1   592.9 1687.73   607.1 1691.88   658.4 1691.56
   726.8 1695.21     867 1707.34   894.3 1711.23   942.2  1721.41014.058 1741.16
#Mann= 9 ,-1 , 0
       0      .1       0     120     .04       0     220      .1       0
  321.17    .035       0  363.92    .045       0  381.33    .035       0
  531.17      .1       0   637.1    .035       0   737.1      .1       0
Bank Sta=363.92,381.33
XS Rating Curve= 0 ,0
Exp/Cntr(USF)=0,0
Exp/Cntr=0.3,0.1

Type RM Length L Ch R = 1 ,15344   ,308.9,300.5,296.1
XS GIS Cut Line= 4
2045707.93119209250589.2934929572045439.01088217250686.104804528
2045051.76563589 250841.002903042044729.06126399251000.203726512
#Sta/Elev= 30
       0 1770.12      27 1759.27    59.1 1749.58    87.3 1738.46   118.1 1728.99
   128.1  1723.5   138.6 1724.16     154 1722.83   166.8 1718.34     285 1694.41
     363 1685.43   376.9 1681.82   388.2 1674.69   398.3 1673.72   405.9 1671.35
   415.8 1671.17   426.4 1669.87   444.4 1671.16   453.8 1674.81     550 1673.73
   562.4 1676.79   578.3  1683.2     603 1688.07     649 1688.28   740.1 1691.93
   797.1 1697.67   884.9 1713.11   929.1 1723.97  1027.5 1751.691062.729 1759.43
#Mann= 9 ,-1 , 0
       0      .1       0     160     .04       0     260      .1       0
   415.8    .045       0   444.4      .1       0  475.82    .035       0
  792.89      .1       0  902.89     .05       0 1012.89      .1       0
Bank Sta=415.8,444.4
XS Rating Curve= 0 ,0
Exp/Cntr(USF)=0,0
Exp/Cntr=0.3,0.1

Type RM Length L Ch R = 1 ,15043   ,231.3,228.5,225.8
XS GIS Cut Line= 4
2045546.57900614250283.8000208912045264.75052135250406.427682213
2045021.64656118250589.2934929572044649.46085226250877.576065189
#Sta/Elev= 30
       0 1757.24    48.5 1740.91   104.7 1724.28   116.5 1716.51     138 1716.35
   142.1 1715.27     152 1710.19   166.6 1705.96   198.8  1698.1   241.7 1689.48
   263.2 1687.62   271.7 1685.73   330.1 1681.45   342.9 1678.87   363.4 1672.24
   375.8  1670.1  379.151668.608     384 1667.53  407.261668.606     425 1671.34
   476.8  1671.3   498.9 1674.67   548.2 1677.17   596.8 1683.32   698.9 1685.53
   742.2  1687.7   800.7 1693.44   845.1 1700.67   887.8  1710.41082.329 1769.43
#Mann= 8 ,-1 , 0
       0      .1       0      90     .04       0     200      .1       0
  379.15    .045       0  407.26      .1       0  557.35    .035       0
  891.55     .05       0 1051.55      .1       0
Bank Sta=379.15,407.26
XS Rating Curve= 0 ,0
Exp/Cntr(USF)=0,0
Exp/Cntr=0.5,0.3

Type RM Length L Ch R = 1 ,14815   ,51.2,52.2,54.9
XS GIS Cut Line= 4
2045410.76480537250095.040417529 2045103.3983354250238.621408824
2044987.22476151 250350.492257752044608.58496515250750.645678908
#Sta/Elev= 30
       0 1733.55    36.8 1719.37    47.7 1712.03    69.4 1712.28   145.4 1693.36
   201.2 1686.29   255.4 1680.39   304.8 1676.94   345.4 1675.49   382.6 1672.54
   394.2 1670.63  401.42 1667.28   405.2 1665.72   410.4 1664.94   423.4 1664.75
     428 1665.21  435.291667.278   441.6 1668.24   454.5 1668.76   523.5 1669.43
   604.8  1672.7     668 1676.72   768.2 1687.09   821.2 1690.93   865.3 1697.34
   897.8 1703.95   925.6 1710.97   975.2 1724.97  1029.4 1742.091051.429 1747.94
#Mann= 13 ,-1 , 0
       0     .06       0      50     .04       0     170      .1       0
     270    .035       0  379.25      .1       0  389.25    .035       0
  401.42    .045       0  435.29    .035       0  530.53     .04       0
  660.53    .035       0  670.53     .04       0  930.53      .1       0
  960.53     .05       0
#XS Ineff= 2 , 0
             385 1674.43     450         1674.43
Permanent Ineff=
       F       F
Bank Sta=401.42,435.29
XS Rating Curve= 0 ,0
Exp/Cntr(USF)=0,0
Exp/Cntr=0.5,0.3

Type RM Length L Ch R = 1 ,14763   ,161,155.7,145.6
XS GIS Cut Line= 4
2045383.07545771250034.2419732872045062.52244829250208.502334114
2044899.01889986250359.0977076682044580.61725292250690.407529486
#Sta/Elev= 30
       0  1735.7    25.1 1724.73    36.3 1715.28    40.1 1713.21    58.6 1713.22
    77.9 1709.85   111.8  1701.2   118.5 1699.02   129.7 1693.49   140.9 1691.02
   163.3 1688.37   196.9 1682.12     230 1678.34   298.7 1675.11   393.6 1672.58
   415.1 1670.34  421.071667.186   427.4 1664.92  468.431667.185   587.1 1671.43
   663.8 1675.91   762.7 1683.47   820.7 1689.73   857.7 1695.08   883.3 1696.06
   899.6 1699.63   930.6 1701.93   944.2  1708.4   990.5 1718.891046.652 1735.59
#Mann= 12 ,-1 , 0
       0      .1       0      20     .04       0     280    .035       0
     360     .04       0  421.07    .045       0  468.43    .035       0
  494.86     .04       0  627.15      .1       0  737.15     .04       0
  767.15     .06       0  867.15     .04       0  907.15     .05       0
#XS Ineff= 2 , 0
             410 1674.43     479         1674.43
Permanent Ineff=
       F       F
Bank Sta=421.07,468.43
XS Rating Curve= 0 ,0
Exp/Cntr(USF)=0,0
Exp/Cntr=0.5,0.3

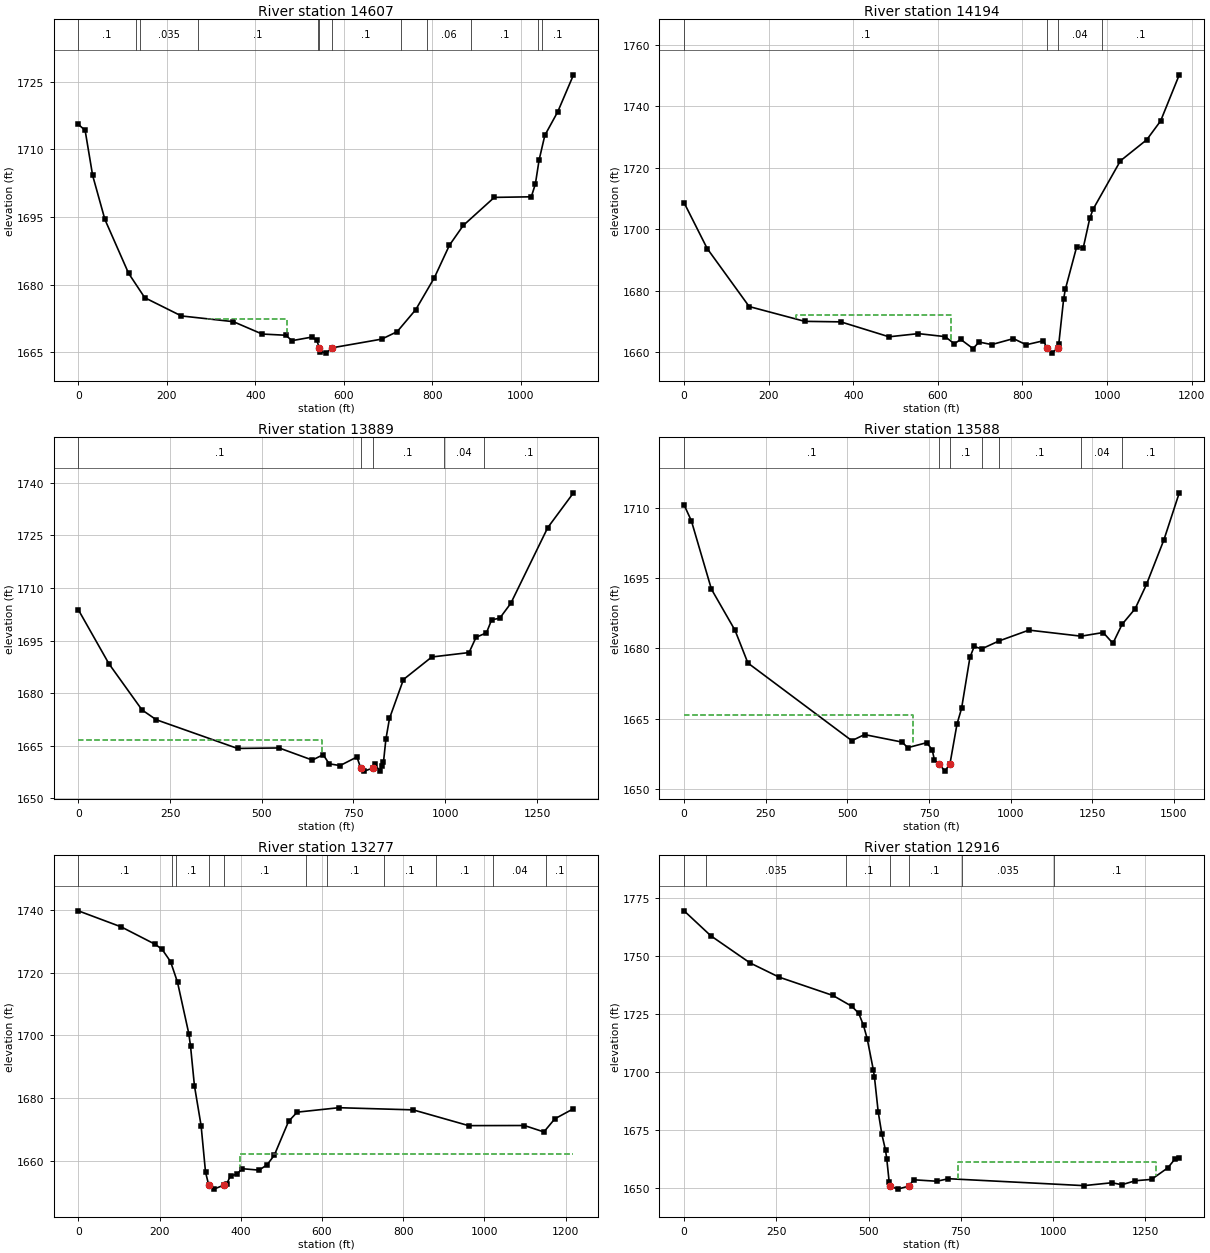
Type RM Length L Ch R = 1 ,14607   ,400.7,412.7,419
XS GIS Cut Line= 4
 2045267.2454136249788.0173232972044930.34204934250103.622199017
2044800.61489183250289.4999172322044529.54321944250624.467055265
#Sta/Elev= 30
       0 1715.56    15.4 1714.25    32.4 1704.23    60.1 1694.45   113.6  1682.5
   150.2 1677.07   232.9 1673.02   350.4 1671.75   415.5    1669   468.9 1668.73
     483 1667.53   527.8 1668.32     539 1667.62  544.671665.928     547 1665.07
   560.8 1664.76  572.861665.927   685.7 1667.87   720.6 1669.52   762.7 1674.42
   804.7  1681.5   838.9 1688.74     870 1693.11   940.2 1699.35  1023.9 1699.48
  1033.1 1702.35  1041.5 1707.66  1054.4 1713.12  1083.7 1718.381119.219 1726.57
#Mann= 12 ,-1 , 0
       0      .1       0     130     .04       0     140    .035       0
     270      .1       0  541.64     .04       0  544.67    .045       0
  572.86      .1       0  728.31     .04       0  788.31     .06       0
  888.31      .1       0 1038.31     .05       0 1048.31      .1       0
#XS Ineff= 1 ,-1
291.6622  471.961672.249
Permanent Ineff=
       T
Bank Sta=544.67,572.86
XS Rating Curve= 0 ,0
Exp/Cntr(USF)=0,0
Exp/Cntr=0.3,0.1

Type RM Length L Ch R = 1 ,14194   ,293.2,305.5,313.7
XS GIS Cut Line= 4
2045255.62805621249737.6754412812044548.90548175 250093.94106786
2044382.39002585250196.5610581242044237.17305849250308.862179546
#Sta/Elev= 30
       0 1708.68    54.7 1693.77   153.9 1674.92   285.2 1670.11   370.6 1669.94
   484.5 1665.09   553.9 1666.12   616.8 1665.15   638.9 1662.84   654.1 1664.23
   682.9 1661.27   697.6 1663.38   727.3 1662.56   778.6  1664.5   808.7  1662.5
   849.5  1663.8   857.6 1661.53   870.3 1659.78   883.7  1661.6   885.8 1662.78
   897.3 1677.41   901.2 1680.47   928.1 1694.35   943.6 1693.99     959 1703.56
   966.7 1706.51  1031.5 1722.29  1093.7 1729.13  1126.5 1735.241170.614 1750.24
#Mann= 4 ,-1 , 0
       0      .1       0   857.6    .045       0   883.7     .04       0
  987.04      .1       0
#XS Ineff= 1 ,-1
 265.249630.0199 1672.11
Permanent Ineff=
       T
Bank Sta=857.6,883.7
XS Rating Curve= 0 ,0
Exp/Cntr(USF)=0,0
Exp/Cntr=0.3,0.1

Type RM Length L Ch R = 1 ,13889   ,297.1,301.2,302.3
XS GIS Cut Line= 5
2045259.50050868249706.6958215782044606.99226869249826.741847925
2044355.28285861249842.2316577772044226.28535059249857.864544282
2044015.05284335250076.468665634
#Sta/Elev= 30
       01703.817    83.6 1688.38  173.671675.242 212.3911672.448 433.8691664.263
  547.291664.401 637.8391660.942 667.3251662.481  683.761659.884 713.3431659.375
 759.3621661.828  769.861658.612 779.0841657.795 802.0931658.633 808.6671659.756
 821.0911657.858 828.3891659.199 831.6761660.314 838.251 1666.87 848.1121672.821
 886.1171683.911 963.4151690.3341064.9511691.5951084.0011695.9431112.3291697.217
1126.4941700.931 1148.561701.3841178.7231705.6311279.3761727.2071349.5711737.129
#Mann= 5 ,-1 , 0
       0      .1       0  769.86    .045       0 802.093      .1       0
  995.64     .04       0 1105.59      .1       0
#XS Ineff= 2 , 0
           663.1 1666.59
Permanent Ineff=
       F       F
Bank Sta=769.86,802.093
XS Rating Curve= 0 ,0
Exp/Cntr(USF)=0,0
Exp/Cntr=0.3,0.1

Type RM Length L Ch R = 1 ,13588   ,330.8,311,267.9
XS GIS Cut Line= 4
2045280.79899722249571.1599853792044684.44131795249563.415080454
2044370.77266846249542.1165919082043985.01613371250008.674132667
#Sta/Elev= 30
       01710.557  22.4151707.158  83.7221692.618 156.0251683.852 195.3991676.893
 513.6661660.354 552.4461661.651 668.0371660.049 684.4791658.861  743.671659.942
 760.1121658.297 766.6891656.186   779.81655.477 798.9931653.872   814.31655.494
 835.7451663.921 849.6271667.228 875.2061678.078 888.3591680.432 910.7991679.886
 963.1921681.5611055.8691683.8981215.4791682.6071283.2241683.3831313.023 1681.09
1341.114 1685.131381.1361688.4551415.6841693.6151469.2811703.1431516.1781713.129
#Mann= 7 ,-1 , 0
       0      .1       0   779.8    .045       0   814.3      .1       0
 910.799      .1       0 963.192      .1       01215.479     .04       0
1341.114      .1       0
#XS Ineff= 2 , 0
             700 1665.83
Permanent Ineff=
       F       F
Bank Sta=779.8,814.3
XS Rating Curve= 0 ,0
Exp/Cntr(USF)=0,0
Exp/Cntr=0.3,0.1

Type RM Length L Ch R = 1 ,13277   ,370.6,360.5,341.3
XS GIS Cut Line= 3
 2044717.3453812  248994.93431892044385.31413117249435.472513318
2043927.41482562249921.583624437
#Sta/Elev= 30
       0 1739.71   105.6 1734.59   189.8    1729   206.5 1727.39   227.1 1723.53
   244.3 1716.94   272.2 1700.49   276.4 1696.51     286  1683.9   302.4 1671.18
   313.3 1656.35   321.1 1652.25   333.9 1650.91   358.6 1652.19   365.6 1652.59
     375 1655.22   391.4 1655.62   402.3 1657.44   445.3 1656.97   465.3 1658.72
   482.8 1661.77   517.9 1672.55     539 1675.47   641.7 1676.89   824.6  1676.2
   961.3 1671.17  1098.5 1671.21  1146.6 1669.16  1173.6 1673.35  1219.5 1676.57
#Mann= 11 ,-1 , 0
       0      .1       0     230      .1       0     240      .1       0
   321.1    .045       0   358.6      .1       0  561.65      .1       0
  611.65      .1       0  751.65      .1       0  881.65      .1       0
 1021.65     .04       0 1151.65      .1       0
#XS Ineff= 2 , 0
                          399.17         1662.22
Permanent Ineff=
       F       F
Bank Sta=321.1,358.6
XS Rating Curve= 0 ,0
Exp/Cntr(USF)=0,0
Exp/Cntr=0.3,0.1

Type RM Length L Ch R = 1 ,12916   ,355.2,352,339.7
XS GIS Cut Line= 4
2044479.20133742248750.2000632622044181.02249778249102.593237379
2044148.10665185249340.7490638422043860.69344558249912.411908514
#Sta/Elev= 30
       0 1769.48    72.5 1758.71   178.9    1747   257.3 1740.89   403.4 1732.97
   454.2 1728.33   473.1 1725.34   486.3 1720.03   496.2 1714.33   512.8 1700.93
   515.9 1697.78     526 1682.83     536 1673.09   545.9 1666.19   549.2  1662.6
   555.9 1652.37  558.411650.747     579 1649.44  608.971650.745   622.1 1653.47
   685.1 1652.84   716.2 1653.93  1083.4 1650.95  1159.4 1652.19  1186.2 1651.34
  1222.9 1653.06  1266.7 1653.64  1311.1 1658.65  1329.5  1662.3  1341.9 1662.73
#Mann= 7 ,-1 , 0
       0     .04       0      60    .035       0     440      .1       0
  558.41    .045       0  608.97      .1       0  752.04    .035       0
 1002.04      .1       0
#XS Ineff= 1 ,-1
  742.13 1278.331661.344
Permanent Ineff=
       T
Bank Sta=558.41,608.97
XS Rating Curve= 0 ,0
Exp/Cntr(USF)=0,0
Exp/Cntr=0.3,0.1

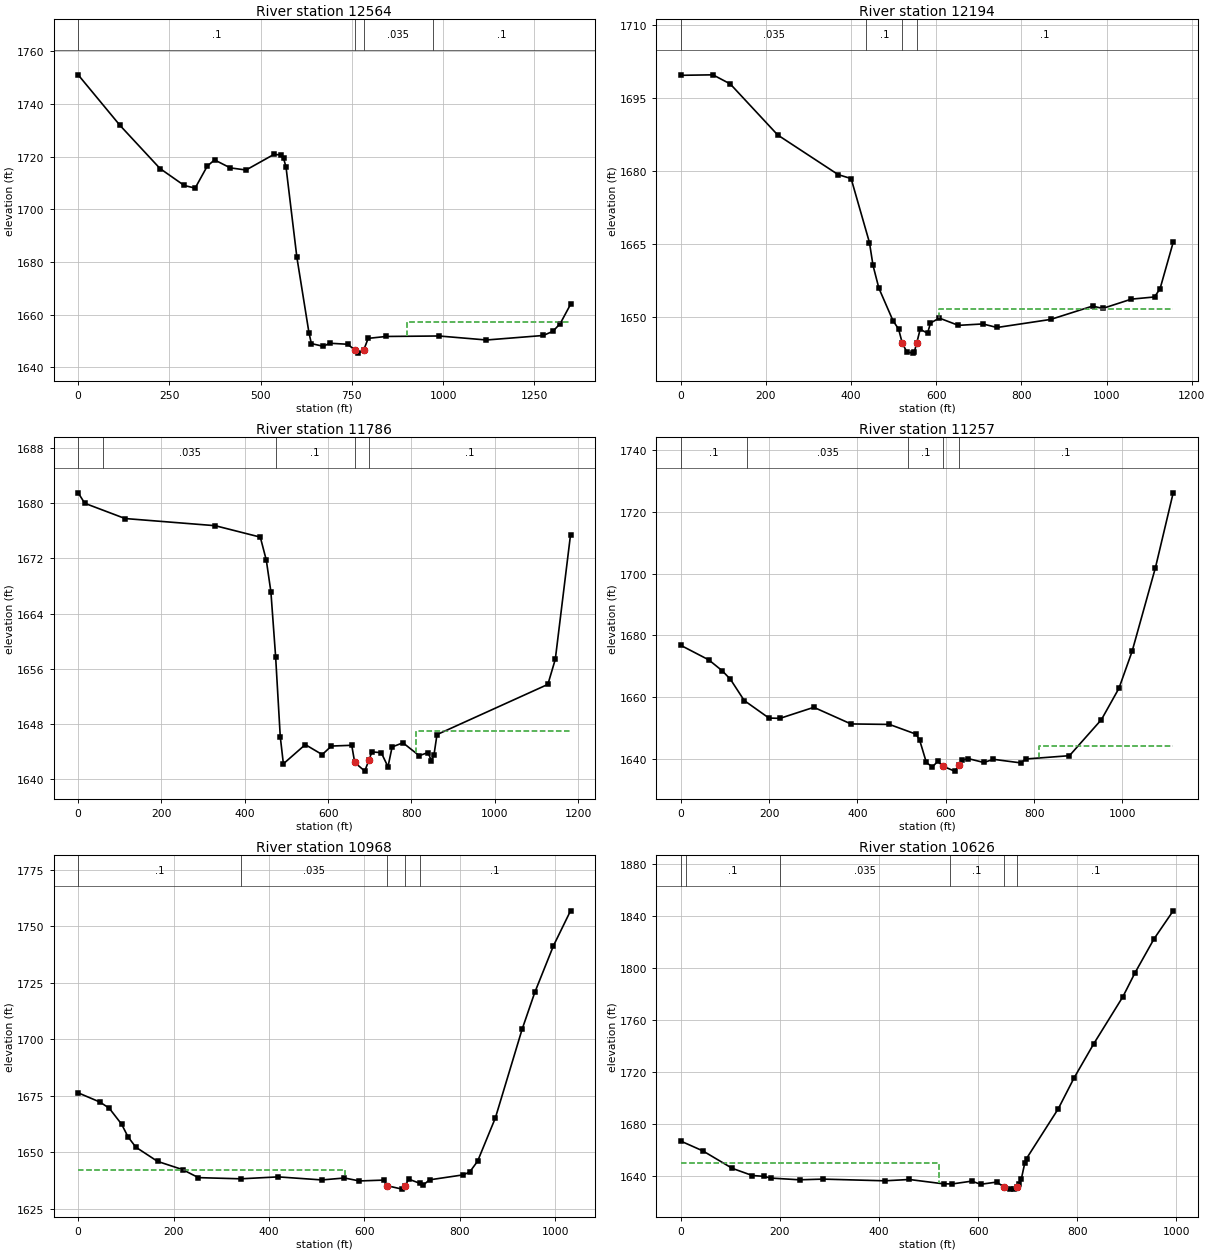
Type RM Length L Ch R = 1 ,12564   ,377.4,369.9,354.8
XS GIS Cut Line= 4
2043969.97383856248616.6004532952043884.77988438249168.424929247
2043847.99158598249439.4966016442043780.68039491  249952.4448842
#Sta/Elev= 30
       0 1751.07   114.8 1731.84   224.4 1715.47   290.7 1709.04   320.6 1708.05
   353.8 1716.39   373.7 1718.76   416.9 1715.73   460.1 1714.92   536.4 1720.84
   556.3 1720.65     563 1719.31   569.6 1716.05   599.4 1681.74   632.5  1653.1
   639.1    1649   672.2 1647.94   688.8 1649.13   738.4 1648.74  757.761646.643
   768.2 1645.37  782.891646.643   794.7 1650.98   844.4  1651.7   988.7 1651.88
    1119 1650.36  1274.5 1652.07    1301 1653.66  1320.9 1656.56  1349.3 1663.88
#Mann= 4 ,-1 , 0
       0      .1       0  757.76    .045       0  782.89    .035       0
  971.92      .1       0
#XS Ineff= 2 , 0
                             900        1657.141
Permanent Ineff=
       F       F
Bank Sta=757.76,782.89
XS Rating Curve= 0 ,0
Exp/Cntr(USF)=0,0
Exp/Cntr=0.3,0.1

Type RM Length L Ch R = 1 ,12194   ,412.3,408,403.3
XS GIS Cut Line= 4
 2043405.0806471248866.8924430782043508.36965503249280.048474776
2043576.24528881249480.7242616012043705.98965748249983.054737402
#Sta/Elev= 30
       0 1699.63    75.4 1699.73     116 1697.86   227.6 1687.36   369.6 1679.21
     400  1678.4   443.1 1665.23   451.4 1660.55   465.2 1655.86   498.5 1649.15
   511.4 1647.48  520.181644.551     531 1642.74   544.6 1642.51   548.3 1642.74
  553.991644.553   562.2 1647.43   579.5 1646.59   586.4 1648.69     607 1649.72
   651.9 1648.22   709.5 1648.51   742.6 1647.78   868.8 1649.44   967.1 1652.18
     991  1651.7  1058.3 1653.61  1112.8 1654.06  1125.7 1655.78  1156.5  1665.3
#Mann= 4 ,-1 , 0
       0    .035       0  435.87      .1       0  520.18    .045       0
  553.99      .1       0
#XS Ineff= 2 , 0
                             607        1651.657
Permanent Ineff=
       F       F
Bank Sta=520.18,553.99
XS Rating Curve= 0 ,0
Exp/Cntr(USF)=0,0
Exp/Cntr=0.3,0.1

Type RM Length L Ch R = 1 ,11786   ,508.1,529.1,523.6
XS GIS Cut Line= 4
2042929.95121065248934.7680768572043068.65359272249356.777452092
2043228.01377637249651.8889033052043381.47173101250023.729331833
#Sta/Elev= 30
       0 1681.53    15.9 1680.01   112.6  1677.8     329 1676.76   437.2  1675.1
   451.6 1671.76   462.6 1667.19     474 1657.74   485.1 1646.15   492.6  1642.2
   545.2 1644.99   585.8 1643.54   607.9 1644.78   656.7 1644.89   663.8  1642.4
     688 1641.14   697.7 1642.72   705.1 1643.93   727.5 1643.82   743.7 1641.77
   753.6 1644.65   779.7 1645.25   818.7 1643.38     840 1643.84   847.9  1642.6
   854.2 1643.53   861.3 1646.44  1127.5 1653.73  1145.3 1657.371181.871 1675.45
#Mann= 5 ,-1 , 0
       0     .04       0      60    .035       0  474.22      .1       0
   663.8    .045       0   697.7      .1       0
#XS Ineff= 2 , 0
                             810            1647
Permanent Ineff=
       F       F
Bank Sta=663.8,697.7
XS Rating Curve= 0 ,0
Exp/Cntr(USF)=0,0
Exp/Cntr=0.3,0.1

Type RM Length L Ch R = 1 ,11257   ,290.9,288.9,286.8
XS GIS Cut Line= 4
2042561.06189663249097.079375024 2042723.3731948249542.697666356
2042782.39548504249802.3957434232042826.66220272250174.236171951
#Sta/Elev= 30
       0 1676.77    63.3 1672.06    93.6 1668.54   112.2 1665.79   143.6 1658.87
   199.5 1653.19   224.6 1653.09   301.2 1656.67   385.3 1651.28   472.4 1651.12
   532.5 1647.97   540.8 1646.05     556 1638.79   569.5 1637.31   581.9 1639.15
   592.9  1637.6     620 1635.97  630.561637.826   636.8 1639.48   650.2 1640.05
   686.1 1638.78     708  1639.8   770.4 1638.63   780.7  1639.9   880.1 1640.98
   952.5 1652.68   992.2 1662.85  1021.9 1674.79  1074.8 1701.971115.045 1726.25
#Mann= 5 ,-1 , 0
       0      .1       0     150    .035       0  514.26      .1       0
   592.9    .045       0  630.56      .1       0
#XS Ineff= 2 , 0
                             810            1644
Permanent Ineff=
       F       F
Bank Sta=592.9,630.56
XS Rating Curve= 0 ,0
Exp/Cntr(USF)=0,0
Exp/Cntr=0.3,0.1

Type RM Length L Ch R = 1 ,10968   ,324.9,342,360.6
XS GIS Cut Line= 4
2042457.77288871 249147.248321732042457.77288871249672.546704889
2042522.69740798249882.0758352512042572.86635468250165.382828415
#Sta/Elev= 30
       0 1676.25    45.4 1672.19    65.1 1669.46    91.3  1662.3   104.5 1656.78
   120.9  1652.2   166.5  1645.9   219.3 1642.24   252.1 1638.71     341 1638.19
   419.4 1639.04     511 1637.69   558.4 1638.55   589.6 1637.24   641.2 1637.62
  647.671635.149   678.9 1633.62  686.32 1635.15   692.7 1638.08   715.8 1636.23
   723.6 1635.44   736.7 1637.73   807.5 1639.94     821 1641.21   837.5 1645.98
   874.8 1665.16   930.8 1704.36   957.4  1720.7   996.5 1741.33 1032.37 1756.83
#Mann= 5 ,-1 , 0
       0      .1       0     341    .035       0  647.67    .045       0
  686.32    .035       0   715.8      .1       0
#XS Ineff= 2 , 0
             560    1642
Permanent Ineff=
       F       F
Bank Sta=647.67,686.32
XS Rating Curve= 0 ,0
Exp/Cntr(USF)=0,0
Exp/Cntr=0.3,0.1

Type RM Length L Ch R = 1 ,10626   ,218.1,216.3,216.3
XS GIS Cut Line= 4
2042369.23945334249182.6616958762042230.53707127249666.644475865
2042121.34583433249926.3425529332042047.56797152250121.116110733
#Sta/Elev= 30
       0 1666.69    44.5 1659.14   103.9 1645.68   144.2 1640.18     168 1639.54
     181 1638.22   239.5 1636.87   286.8 1637.41   411.6  1636.1   460.9 1637.12
   530.3 1633.75   548.1 1633.72     587 1635.84     605 1633.42   637.2 1635.12
  651.461631.543   664.7 1629.69   672.6 1629.95  679.251631.544   683.3 1633.78
   686.9 1637.31     694  1649.8   697.5 1653.26   761.6 1691.62   793.5 1715.42
   833.3 1741.79   891.9 1777.91   916.3  1796.3   954.9 1822.59993.4635 1844.12
#Mann= 6 ,-1 , 0
       0     .04       0      10      .1       0     200    .035       0
  543.47      .1       0  651.46    .045       0  679.25      .1       0
#XS Ineff= 2 , 0
             520    1650
Permanent Ineff=
       F       F
Bank Sta=651.46,679.25
XS Rating Curve= 0 ,0
Exp/Cntr(USF)=0,0
Exp/Cntr=0.3,0.1