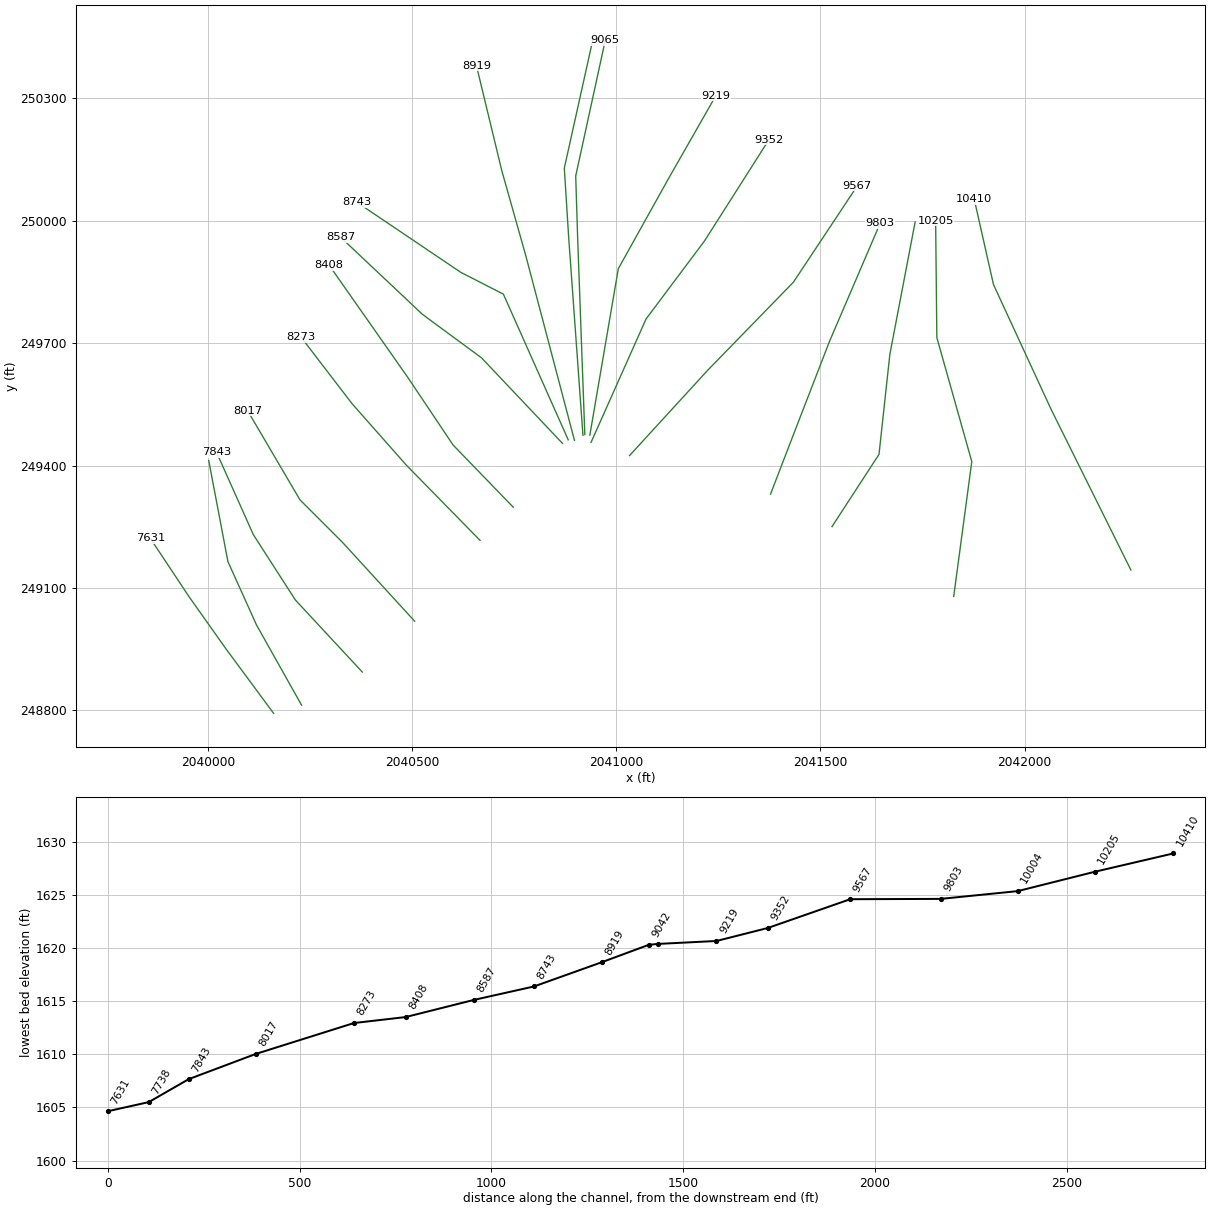
HEC-RAS study HNGRDCK_1.prj: HNGRDCK_1

--- HNGRDCK_1.g01 (geometry) --- (continued)

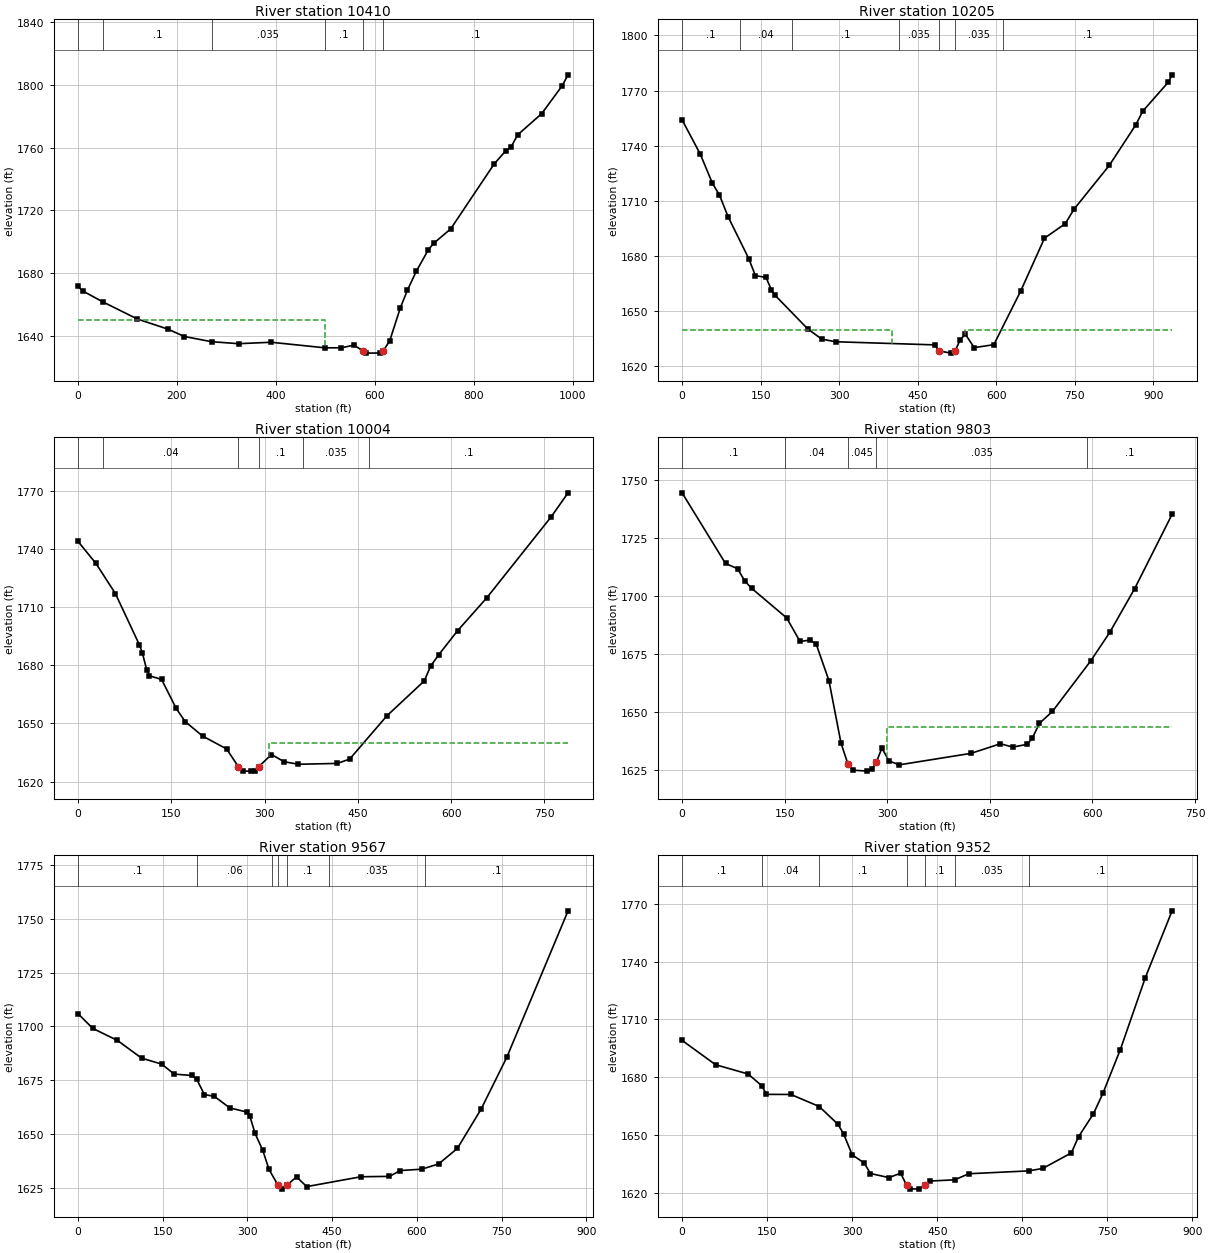
Type RM Length L Ch R = 1 ,10410   ,207.6,205.3,200.6
XS GIS Cut Line= 4
 2042260.0482164249144.297207218 2042065.2746586249536.795437332
2041923.62116201249843.7113465932041876.40332982250053.240476954
#Sta/Elev= 30
       0 1671.44      10 1668.47    50.3 1661.59   119.9 1650.66   182.2 1644.18
   215.1  1639.5   270.1 1636.19   324.5 1634.93   390.6 1635.84   498.9  1632.3
   532.5 1632.29   558.2 1634.02  575.761630.368   583.1  1628.9   610.2 1628.98
  617.091630.366   630.1 1636.57   651.7 1657.73   666.2 1669.15   684.3 1681.27
   707.9 1694.57   718.9 1698.92   753.6 1708.16   841.6 1749.65   865.5 1758.19
   875.6 1760.41   889.1 1768.19   937.7 1781.74   978.9 1799.44990.9803 1806.49
#Mann= 6 ,-1 , 0
       0     .04       0    50.3      .1       0   270.1    .035       0
   498.9      .1       0  575.76    .045       0  617.09      .1       0
#XS Ineff= 2 , 0
             500    1650
Permanent Ineff=
       F       F
Bank Sta=575.76,617.09
XS Rating Curve= 0 ,0
Exp/Cntr(USF)=0,0
Exp/Cntr=0.3,0.1

Type RM Length L Ch R = 1 ,10205   ,209.7,201,188.4
XS GIS Cut Line= 4
2041826.23438311249079.3726879512041870.50110079 249409.89751331
2041784.91877994249713.8623080592041781.96766543250000.120415736
#Sta/Elev= 30
       0 1754.07    34.9 1735.31      58 1719.48    71.3 1713.21    87.8  1701.4
   127.5 1678.47   139.9 1669.34   160.4 1668.33   170.6 1661.48   177.9 1658.53
   240.1 1640.29   266.6  1634.8     293 1633.36   482.1 1631.66  490.991628.362
   513.4 1627.17  521.571628.361   530.4 1634.18   540.7  1637.5   557.7 1630.16
   595.2 1631.77   646.3 1660.83   691.9 1689.69   731.7 1697.62   748.1  1705.4
   815.5 1729.22   866.3 1751.36   879.4 1758.71   928.6 1774.65935.5323 1778.53
#Mann= 7 ,-1 , 0
       0      .1       0     110     .04       0     210      .1       0
  413.48    .035       0  490.99    .045       0  521.57    .035       0
  613.48      .1       0
#XS Ineff= 2 , 0
             400    1640     540            1640
Permanent Ineff=
       F       F
Bank Sta=490.99,521.57
XS Rating Curve= 0 ,0
Exp/Cntr(USF)=0,0
Exp/Cntr=0.3,0.1

Type RM Length L Ch R = 1 ,10004   ,205.4,200.8,191.7
XS GIS Cut Line= 4
2041528.17181739249250.5373296552041643.26528336249427.604200383
2041669.82531397249672.5467048892041731.79871872249997.169301224
#Sta/Elev= 30
       0  1743.8    28.8 1732.47    60.1  1716.9    98.7 1690.46   103.4 1686.36
   110.5 1677.52   114.9 1674.51   134.4 1672.62   157.9 1657.66   172.2 1650.94
   200.2 1643.46   238.9  1636.8  257.761627.688   265.3 1625.36   278.6 1625.35
   285.1 1625.67  290.721627.688   311.1 1633.92   331.3  1630.2   354.4 1628.89
   417.1 1629.33   436.9 1631.58   496.7 1653.88   556.9  1671.9   566.9 1679.44
   580.2 1685.43   610.3 1697.75   657.1 1714.65   760.6 1756.39788.0488 1768.88
#Mann= 6 ,-1 , 0
       0      .1       0      40     .04       0  257.76    .045       0
  290.72      .1       0  361.19    .035       0  467.56      .1       0
#XS Ineff= 2 , 0
                           307.2            1640
Permanent Ineff=
       F       F
Bank Sta=257.76,290.72
XS Rating Curve= 0 ,0
Exp/Cntr(USF)=0,0
Exp/Cntr=0.3,0.1

Type RM Length L Ch R = 1 ,9803    ,242.6,235.6,224.4
XS GIS Cut Line= 4
2041377.66497727249330.2174214822041436.68726751249483.675376113
2041522.26958836249705.0089645232041646.21639787249994.218186712
#Sta/Elev= 30
       0 1744.65    63.5 1714.18    81.1 1711.93    91.6 1706.65     102 1703.39
   152.8 1690.73   172.5 1680.53   186.6 1681.12     196 1679.48   214.7 1663.66
   232.3 1636.76  242.671627.481   249.9 1625.04     271 1624.62     278 1625.63
   283.9 1628.42   292.1 1634.55   302.6 1628.98   317.7 1627.34   422.5 1632.29
   465.4 1636.44   483.2 1634.98   504.6 1636.18   511.8 1638.75   522.5 1645.26
   541.4 1650.36   597.5  1672.2   625.3 1684.49   661.7 1703.36716.3707 1735.39
#Mann= 5 ,-1 , 0
       0      .1       0     150     .04       0  242.67    .045       0
   283.9    .035       0  591.72      .1       0
#XS Ineff= 2 , 0
                             300         1643.61
Permanent Ineff=
       F       F
Bank Sta=242.67,283.9
XS Rating Curve= 0 ,0
Exp/Cntr(USF)=0,0
Exp/Cntr=0.3,0.1

Type RM Length L Ch R = 1 ,9567    ,212,215.1,217.3
XS GIS Cut Line= 4
2041032.38457935249424.6530858712041224.20702264249634.182216232
  2041433.736153249849.6135756172041590.14522214250085.702736588
#Sta/Elev= 30
       0 1705.92    26.1  1699.1    69.8 1693.53   112.5 1685.33   148.1 1682.55
   170.3 1677.92   201.4 1677.28   210.3 1675.46   223.7 1668.45   241.5 1667.59
   268.6 1662.26   299.7 1660.28   304.3  1658.4   313.5  1650.4   327.2 1642.54
   338.2  1633.7  354.041626.471   361.4 1624.59   370.7 1626.62   386.9 1630.26
     405 1625.76   501.1 1630.33   551.5  1630.5   570.6 1633.21   608.6 1633.83
   638.6 1636.28   671.7 1643.46   713.5 1661.54   759.3 1685.72867.7953 1753.62
#Mann= 7 ,-1 , 0
       0      .1       0     210     .06       0  344.07      .1       0
  354.04    .045       0   370.7      .1       0  444.07    .035       0
   614.6      .1       0
Bank Sta=354.04,370.7
XS Rating Curve= 0 ,0
Exp/Cntr(USF)=0,0
Exp/Cntr=0.3,0.1

Type RM Length L Ch R = 1 ,9352    ,130.1,133.5,136.7
XS GIS Cut Line= 4
2040938.07939619249456.9463421022041072.73734741249759.291553344
2041216.28780485249951.1156159382041373.81220063250198.835431871
#Sta/Elev= 30
       0 1699.08    59.1 1686.46   116.5 1681.64   140.5 1675.57   148.8 1671.07
   191.9 1671.02   241.8 1664.77   274.6 1655.62   284.7 1650.65     300  1639.7
   321.2 1635.42   332.2 1629.99   364.9 1627.85   385.4 1630.16  396.081623.849
   402.1 1622.07   418.2 1621.88  428.861623.845   437.3 1626.07   481.1 1626.72
   505.3 1629.86   611.3 1631.35     636 1632.61   686.5 1640.69   699.2 1649.09
   725.4 1660.99     742 1671.52   772.9 1694.35     817 1731.73864.1287 1766.34
#Mann= 7 ,-1 , 0
       0      .1       0   140.5     .04       0   241.8      .1       0
  396.08    .045       0  428.86      .1       0   481.1    .035       0
   611.3      .1       0
Bank Sta=396.08,428.86
XS Rating Curve= 0 ,0
Exp/Cntr(USF)=0,0
Exp/Cntr=0.3,0.1

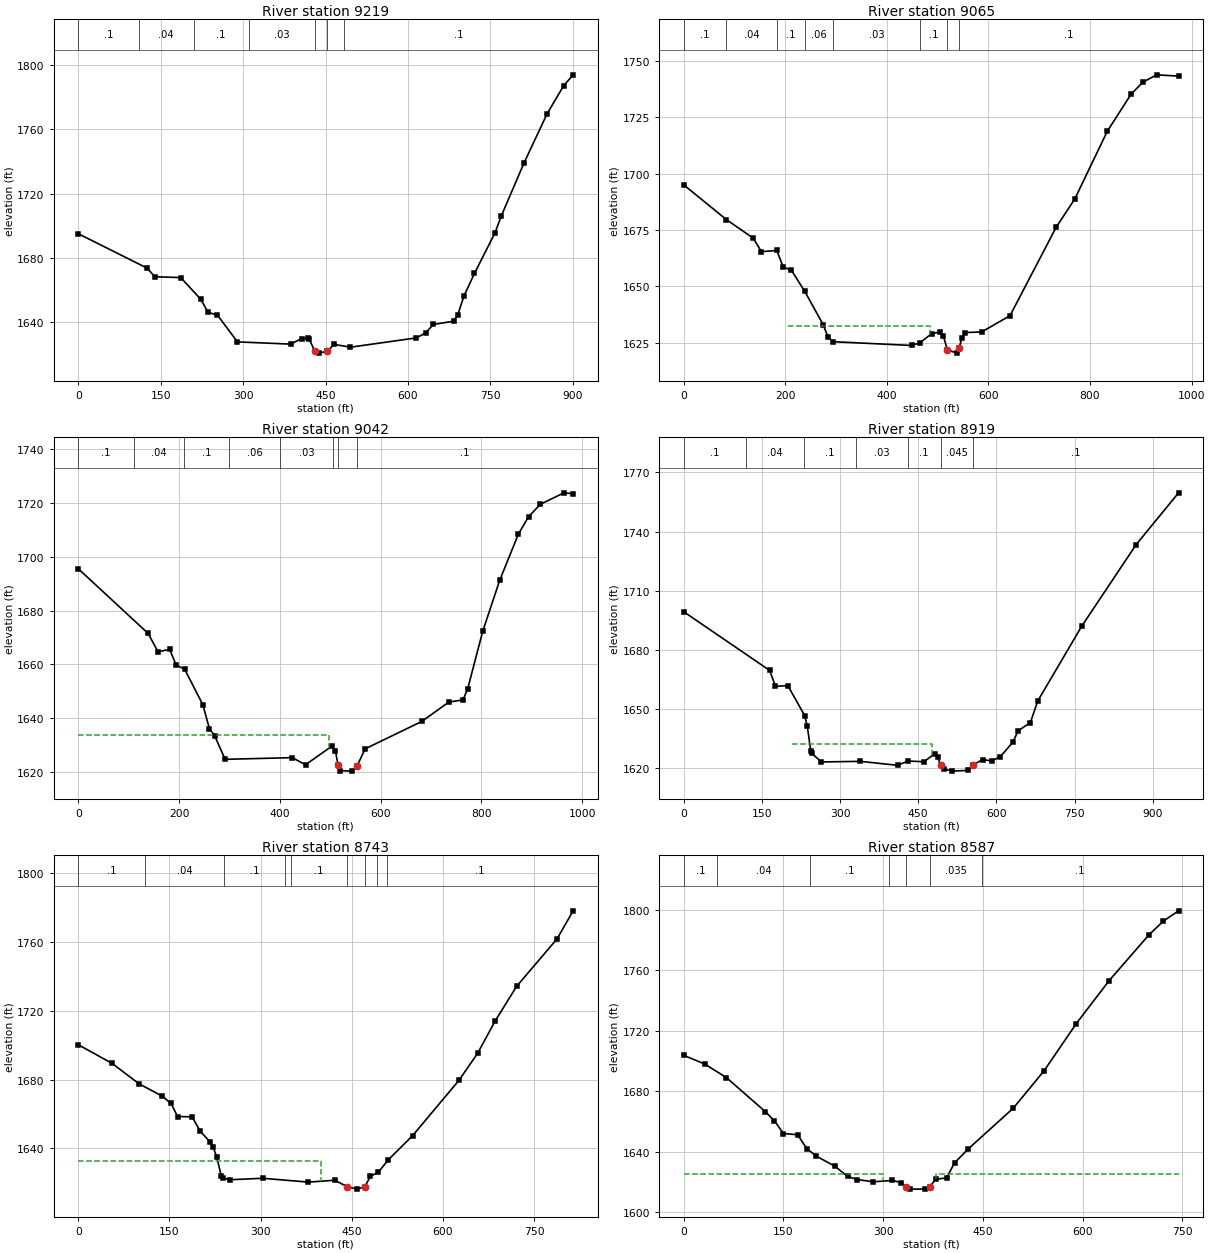
Type RM Length L Ch R = 1 ,9219    ,142.7,153.1,170.8
XS GIS Cut Line= 4
2040935.14128213 249474.798526432041004.92414333249882.759868777
2041129.72810661250106.8702114482041243.79624509250306.824948322
#Sta/Elev= 30
       0 1695.03   125.1 1673.63   139.3 1668.24   186.4 1667.71     223 1654.17
   236.3 1645.97     253 1644.47   289.6 1627.66   386.6 1626.27   406.5 1629.76
   417.2 1629.84   420.1 1629.48   430.2 1622.15   438.9 1620.66   453.4 1621.92
   465.5  1626.1   495.2 1624.36   615.4 1630.15   631.9 1633.23   646.4 1638.55
     683 1640.54   690.6 1644.45   701.9 1656.26     721  1670.3   758.6 1695.77
   769.9 1706.15   811.5 1739.34     853 1769.59   883.2 1787.15   900.6 1793.99
#Mann= 7 ,-1 , 0
       0      .1       0     110     .04       0     210      .1       0
     310     .03       0   430.2    .045       0   453.4     .03       0
  483.89      .1       0
Bank Sta=430.2,453.4
XS Rating Curve= 0 ,0
Exp/Cntr(USF)=0,0
Exp/Cntr=0.5,0.3

Type RM Length L Ch R = 1 ,9065    ,22.8,23.3,25.5
XS GIS Cut Line= 4
2040922.83509982249476.0017125582040905.25148627249958.637064688
2040900.52120575250109.7606170082040972.85414427250442.103835347
#Sta/Elev= 30
       01695.032  84.1651679.603 136.6941671.409 153.109  1665.4 183.3381665.914
 195.7881658.638 212.2031657.108 238.4671647.731  274.581633.016 284.4291627.368
 294.2781625.459 448.5791623.783 464.9951624.927 487.9751629.006 504.3871629.752
 510.9521628.199  518.991621.947 537.2111620.383  542.841622.771 547.0591626.894
 553.6241629.523 586.4481629.747 642.4961637.016 733.091 1676.13 770.0251688.791
  833.821718.736 880.8271735.255 904.4571740.633 931.192 1743.83 974.2771743.258
#Mann= 8 ,-1 , 0
       0      .1       0  84.165     .04       0 183.338      .1       0
 238.467     .06       0 294.278     .03       0 464.995      .1       0
  518.99    .045       0  542.84      .1       0
#XS Ineff= 1 ,-1
205.8265484.2402 1632.43
Permanent Ineff=
       T
Bank Sta=518.99,542.84
XS Rating Curve= 0 ,0
Exp/Cntr(USF)=0,0
Exp/Cntr=0.5,0.3

Type RM Length L Ch R = 1 ,9042    ,118.8,122.8,131.8
XS GIS Cut Line= 4
2040918.25804891249474.3926773612040883.31212192249959.356562039
2040872.61438917250129.0939216762040943.21942532 250447.17317545
#Sta/Elev= 30
       0 1695.55   138.6 1671.49   158.3 1664.65   181.3 1665.59   194.5 1659.63
   210.9 1658.28   247.1 1645.02   260.3 1636.07   270.4 1633.54   291.4 1624.69
   424.7 1625.31     451 1622.68   503.7 1629.64   510.3 1627.93   515.6  1622.4
   520.1 1620.49   543.1  1620.3     553 1622.14   569.4 1628.59   681.7 1638.78
   735.5 1645.99   763.3 1646.77   772.5 1650.67   802.7 1672.33   836.3 1691.23
   873.3 1708.38   893.5 1714.86     917 1719.51     964 1723.77   982.1 1723.42
#Mann= 8 ,-1 , 0
       0      .1       0     110     .04       0     210      .1       0
     300     .06       0     400     .03       0  506.22      .1       0
   515.6    .045       0     553      .1       0
#XS Ineff= 2 , 0
           497.4 1633.57
Permanent Ineff=
       F       F
Bank Sta=515.6,553
XS Rating Curve= 0 ,0
Exp/Cntr(USF)=0,0
Exp/Cntr=0.5,0.3

Type RM Length L Ch R = 1 ,8919    ,143.2,176.6,196.5
XS GIS Cut Line= 4
2040897.42793921249462.0277742232040778.01428435249915.545591086
2040719.57781495250122.6139500462040657.33027146250380.496630223
#Sta/Elev= 30
       0 1699.38   164.9 1669.66   176.1 1661.59   199.9 1661.95     232 1646.81
   237.1 1641.41   243.9 1628.73   245.4  1627.7   264.2 1623.31   338.9 1623.61
   410.2  1621.6   430.5 1623.78     461 1623.41   481.5 1627.46     487 1625.99
   492.9 1621.81   498.5 1619.83   515.6 1618.66   546.2 1619.04   554.8 1621.76
   573.5 1624.51     591 1623.86   607.6 1625.98   631.5 1633.32   641.7 1639.11
   665.1 1643.21   679.2 1654.15   763.6 1692.04   868.2 1733.42949.4205 1759.59
#Mann= 7 ,-1 , 0
       0      .1       0     120     .04       0     230      .1       0
     330     .03       0     430      .1       0   492.9    .045       0
   554.8      .1       0
#XS Ineff= 1 ,-1
208.1354475.4777 1632.43
Permanent Ineff=
       T
Bank Sta=492.9,554.8
XS Rating Curve= 0 ,0
Exp/Cntr(USF)=0,0
Exp/Cntr=0.3,0.1

Type RM Length L Ch R = 1 ,8743    ,161.5,156,152.2
XS GIS Cut Line= 4
2040882.18364285249463.2981322542040723.38888905249820.268738804
2040619.21953055249873.6237760822040365.14792447 250045.12211019
#Sta/Elev= 30
       0 1700.28    55.6 1689.43   100.3 1677.49   138.3 1670.38   152.5 1666.17
   163.4 1658.57   187.3 1658.38   200.6 1650.06   217.3 1643.58   222.1  1640.7
     228 1634.78   235.2  1624.1   238.8 1622.75   249.6 1621.83   303.5 1622.69
   378.7 1620.45   421.8 1621.53  442.64 1617.82   458.7 1616.38   471.5 1617.82
   480.8  1623.9   493.5 1626.12   510.4 1633.52   550.1 1647.46   626.2  1679.5
   656.9 1695.18   686.2 1714.23   721.4 1734.26   787.6 1761.68814.2706 1778.05
#Mann= 9 ,-1 , 0
       0      .1       0     110     .04       0     240      .1       0
     340    .035       0     350      .1       0  442.64    .045       0
   471.5      .1       0   490.7    .035       0  507.74      .1       0
#XS Ineff= 2 , 0
             400    1633
Permanent Ineff=
       F       F
Bank Sta=442.64,471.5
XS Rating Curve= 0 ,0
Exp/Cntr(USF)=0,0
Exp/Cntr=0.3,0.1

Type RM Length L Ch R = 1 ,8587    ,185.1,178.8,169.7
XS GIS Cut Line= 4
2040868.20970452249454.4056260412040670.03385177249664.014701061
 2040525.2130363249770.7247756172040324.49646749249960.008122151
#Sta/Elev= 30
       0 1703.74    31.5 1697.99    64.2 1689.01   122.6 1666.52   136.5 1660.32
     150 1651.93   171.3 1651.16   185.2  1641.9   199.7 1636.95   227.3  1630.3
   246.4  1623.6   260.7 1621.46   285.4 1619.99   313.7 1620.86   327.2  1619.5
  334.76 1616.54   340.1 1615.12   362.2 1615.15  369.771616.542   378.8 1621.56
   395.3 1622.58   407.4 1632.54   428.1 1641.82   495.9 1668.83   542.3 1693.68
   590.3 1724.69   639.9 1753.26   700.1 1783.72   721.1 1792.52  744.24 1799.44
#Mann= 7 ,-1 , 0
       0      .1       0      50     .04       0     190      .1       0
  308.46    .035       0  334.76    .045       0  369.77    .035       0
  448.46      .1       0
#XS Ineff= 2 , 0
             300    1625     380            1625
Permanent Ineff=
       F       F
Bank Sta=334.76,369.77
XS Rating Curve= 0 ,0
Exp/Cntr(USF)=0,0
Exp/Cntr=0.3,0.1

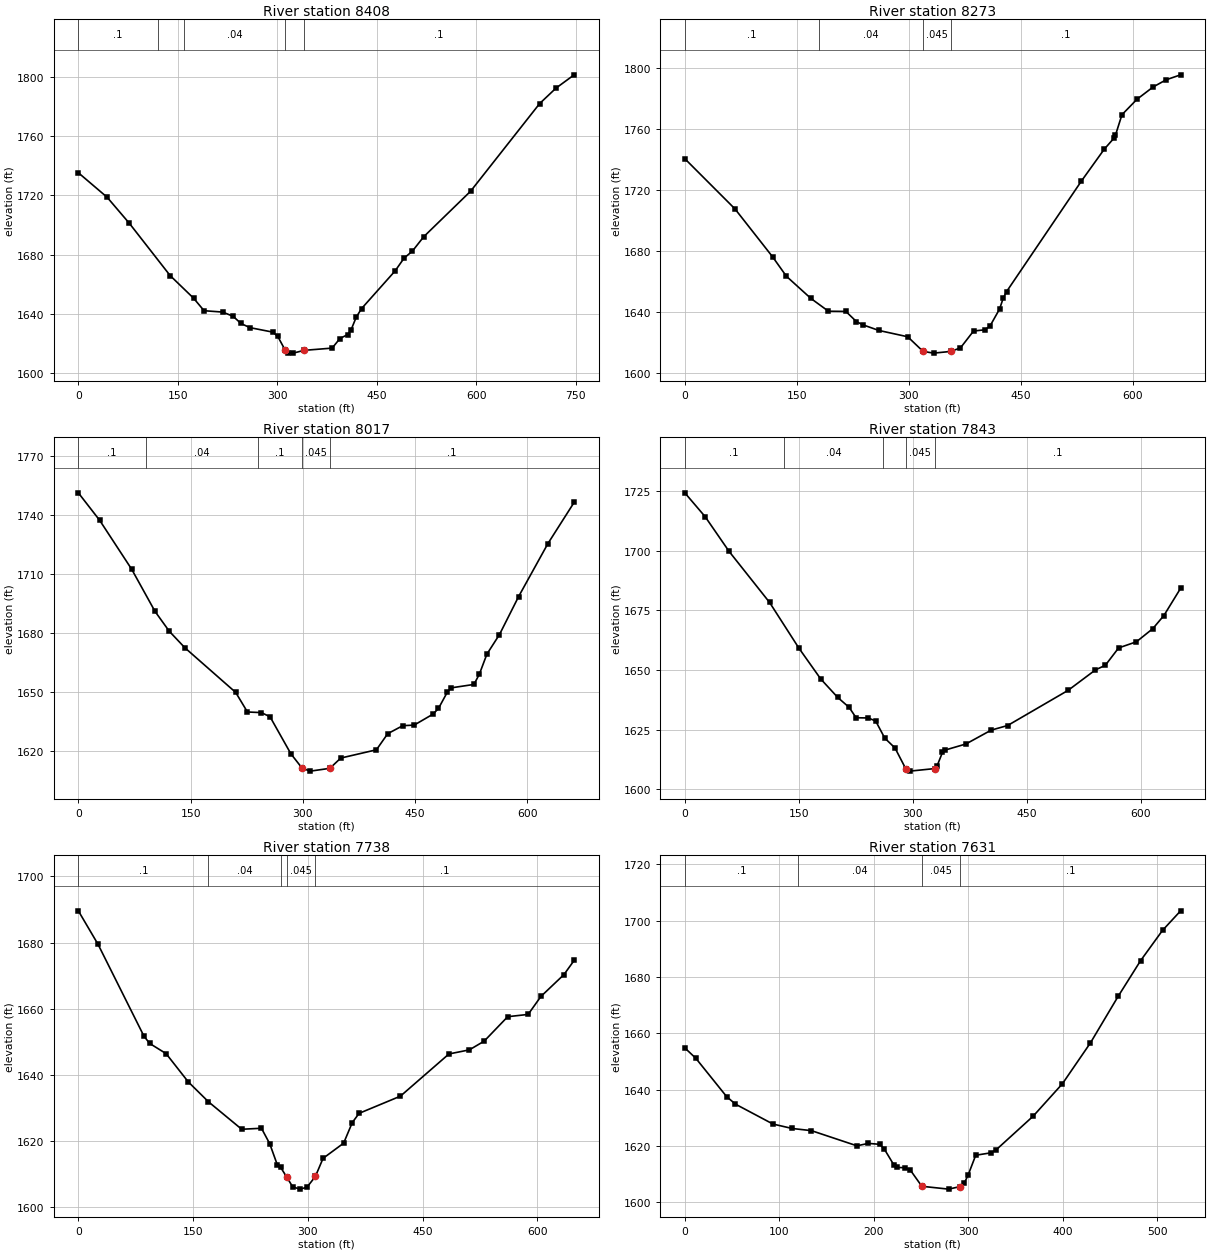
Type RM Length L Ch R = 1 ,8408    ,130.5,134.5,137.4
XS GIS Cut Line= 4
2040747.52569162249298.1515882982040600.16416009 249450.59455195
2040489.64301145249615.7410959052040296.54859082249891.408788508
#Sta/Elev= 30
       0 1735.26    43.3 1718.75    76.9 1701.11   138.4 1665.83   173.8 1650.53
   189.5 1642.13   217.5 1641.21   233.3 1638.37   245.1  1633.5   258.6 1630.71
   293.1 1627.68   300.4 1624.91  311.931615.378   316.2 1613.66   323.8  1613.5
  340.321615.374   382.5 1616.89   394.3 1623.35   406.1 1626.07   410.9 1629.01
   418.9 1637.81   426.9 1643.58   477.3 1668.91     491 1677.64   503.4  1682.3
   520.6 1692.07   591.2 1722.77   695.3 1781.94   719.9 1792.35747.3091 1801.34
#Mann= 5 ,-1 , 0
       0      .1       0     120     .06       0     160     .04       0
  311.93    .045       0  340.32      .1       0
Bank Sta=311.93,340.32
XS Rating Curve= 0 ,0
Exp/Cntr(USF)=0,0
Exp/Cntr=0.3,0.1

Type RM Length L Ch R = 1 ,8273    ,253.4,256.1,257
XS GIS Cut Line= 4
2040666.22277768249216.8486743512040485.83193736249401.050588763
2040352.44434416249552.2231943842040227.94925718249714.829022279
#Sta/Elev= 30
       0 1740.54    67.2 1707.59   117.7 1676.08   136.1 1663.39   168.9 1648.84
   192.4 1640.44   215.8  1640.3   229.9 1633.64   238.2 1631.58   259.9 1627.83
   298.6 1623.68  319.26 1614.06   333.4 1612.94   356.41614.061   369.3 1616.39
   386.8 1627.44   401.8 1628.24   408.7 1630.58   421.7 1641.89   426.6 1649.08
     431 1653.28   531.3 1725.86   561.9 1746.78   574.9    1754   576.8 1755.77
   585.6 1769.39   605.7 1779.51   627.4 1787.62     645 1792.36664.2189 1795.58
#Mann= 4 ,-1 , 0
       0      .1       0     180     .04       0  319.26    .045       0
   356.4      .1       0
Bank Sta=319.26,356.4
XS Rating Curve= 0 ,0
Exp/Cntr(USF)=0,0
Exp/Cntr=0.3,0.1

Type RM Length L Ch R = 1 ,8017    ,176.1,174.7,163.5
XS GIS Cut Line= 4
2040506.15766584249018.6728216042040329.57789961249211.767242229
2040225.40854112249315.9366007242040097.10238005249534.438181958
#Sta/Elev= 30
       0 1751.19    28.5 1737.25    71.3 1712.41   102.4 1691.07   121.4 1681.02
   142.3 1672.61   210.2 1649.96   225.9 1640.03   244.5 1639.71   256.1  1637.6
   283.9 1618.84  299.121611.448     310 1610.03  335.991611.449   350.6 1616.66
   398.2 1620.85   413.3 1629.02   433.4 1633.08   448.6 1633.37   473.9 1638.96
   481.1 1641.83   493.1 1650.21   498.1 1652.27   528.5    1654   535.8 1659.28
   545.8 1669.37   562.6 1679.31   588.2  1698.6   627.3 1725.45662.3654 1746.37
#Mann= 5 ,-1 , 0
       0      .1       0      90     .04       0     240      .1       0
  299.12    .045       0  335.99      .1       0
Bank Sta=299.12,335.99
XS Rating Curve= 0 ,0
Exp/Cntr(USF)=0,0
Exp/Cntr=0.3,0.1

Type RM Length L Ch R = 1 ,7843    ,107.2,104.1,100.8
XS GIS Cut Line= 4
2040377.85150477248894.1777346222040213.97531884249070.757500852
2040111.07631838249230.8226126862040020.88089822249432.809539524
#Sta/Elev= 30
       0 1724.25    26.8 1714.25    58.3  1699.7   111.6 1678.31   150.1  1659.2
   178.9 1646.25   201.3 1638.51   216.2 1634.38   225.4 1630.03   241.5 1629.93
   251.2 1628.63   263.1 1621.49   276.6 1617.35  290.571608.745   296.1 1607.66
  329.441608.746   331.9  1609.8     339 1615.49   342.9 1616.52   369.9 1619.03
   403.1 1624.83   424.8 1626.77   504.4 1641.51   540.3 1650.06   553.4 1652.02
   570.8 1659.27   594.2 1661.84   615.8 1667.35   630.4 1672.85652.4031 1684.27
#Mann= 5 ,-1 , 0
       0      .1       0     130     .04       0  260.91      .1       0
  290.57    .045       0  329.44      .1       0
Bank Sta=290.57,329.44
XS Rating Curve= 0 ,0
Exp/Cntr(USF)=0,0
Exp/Cntr=0.3,0.1

Type RM Length L Ch R = 1 ,7738    ,102.8,107,112.7
XS GIS Cut Line= 4
2040229.21961521248812.8748206752040118.69846656249009.780315391
2040048.82877489249164.7639951032040001.82552776249412.483811037
#Sta/Elev= 30
       0 1689.59    25.7 1679.49    85.6 1651.79    93.1 1649.54   114.7 1646.44
   143.6 1637.92   170.1 1631.88   213.5 1623.59   239.3 1623.89   250.1 1619.23
   260.2 1612.73   264.5 1612.04   272.6 1609.03   280.1  1606.2   289.6  1605.5
   298.8 1606.07   309.8 1609.34   319.8  1614.8   346.7 1619.39     358 1625.62
   366.9  1628.4   420.9 1633.59   484.3 1646.34     511 1647.58   530.4 1650.22
   561.1  1657.6   587.8 1658.29   604.5 1663.72   634.6 1670.32647.9471 1674.62
#Mann= 5 ,-1 , 0
       0      .1       0   170.1     .04       0   264.5      .1       0
   272.6    .045       0   309.8      .1       0
Bank Sta=272.6,309.8
XS Rating Curve= 0 ,0
Exp/Cntr(USF)=0,0
Exp/Cntr=0.3,0.1

Type RM Length L Ch R = 1 ,7631    ,154,154.3,160.5
XS GIS Cut Line= 4
2040160.74820717248792.8166657252040043.08765303248952.277679889
2039953.29407223249079.2272251462039858.85599588249221.658422263
#Sta/Elev= 30
       0 1654.78    11.7 1651.08    44.2 1637.51    53.6 1634.81    93.3 1627.74
   113.6 1626.17     134  1625.4   182.1 1620.02   194.3 1620.88   206.1 1620.55
   210.8 1619.02   221.4 1613.12   224.9 1612.33   232.8 1612.25   238.5 1611.45
   250.8 1605.65   279.1 1604.64   291.7 1605.57   295.7 1606.79   299.7 1609.57
   307.8 1616.67   323.7 1617.52   329.4 1618.59   368.6 1630.55   399.5 1642.04
   429.2 1656.57   458.5 1673.08   482.2 1685.73   505.5 1696.52   524.6 1703.44
#Mann= 4 ,-1 , 0
       0      .1       0     120     .04       0   250.8    .045       0
   291.7      .1       0
Bank Sta=250.8,291.7
XS Rating Curve= 0 ,0
Exp/Cntr(USF)=0,0
Exp/Cntr=0.3,0.1