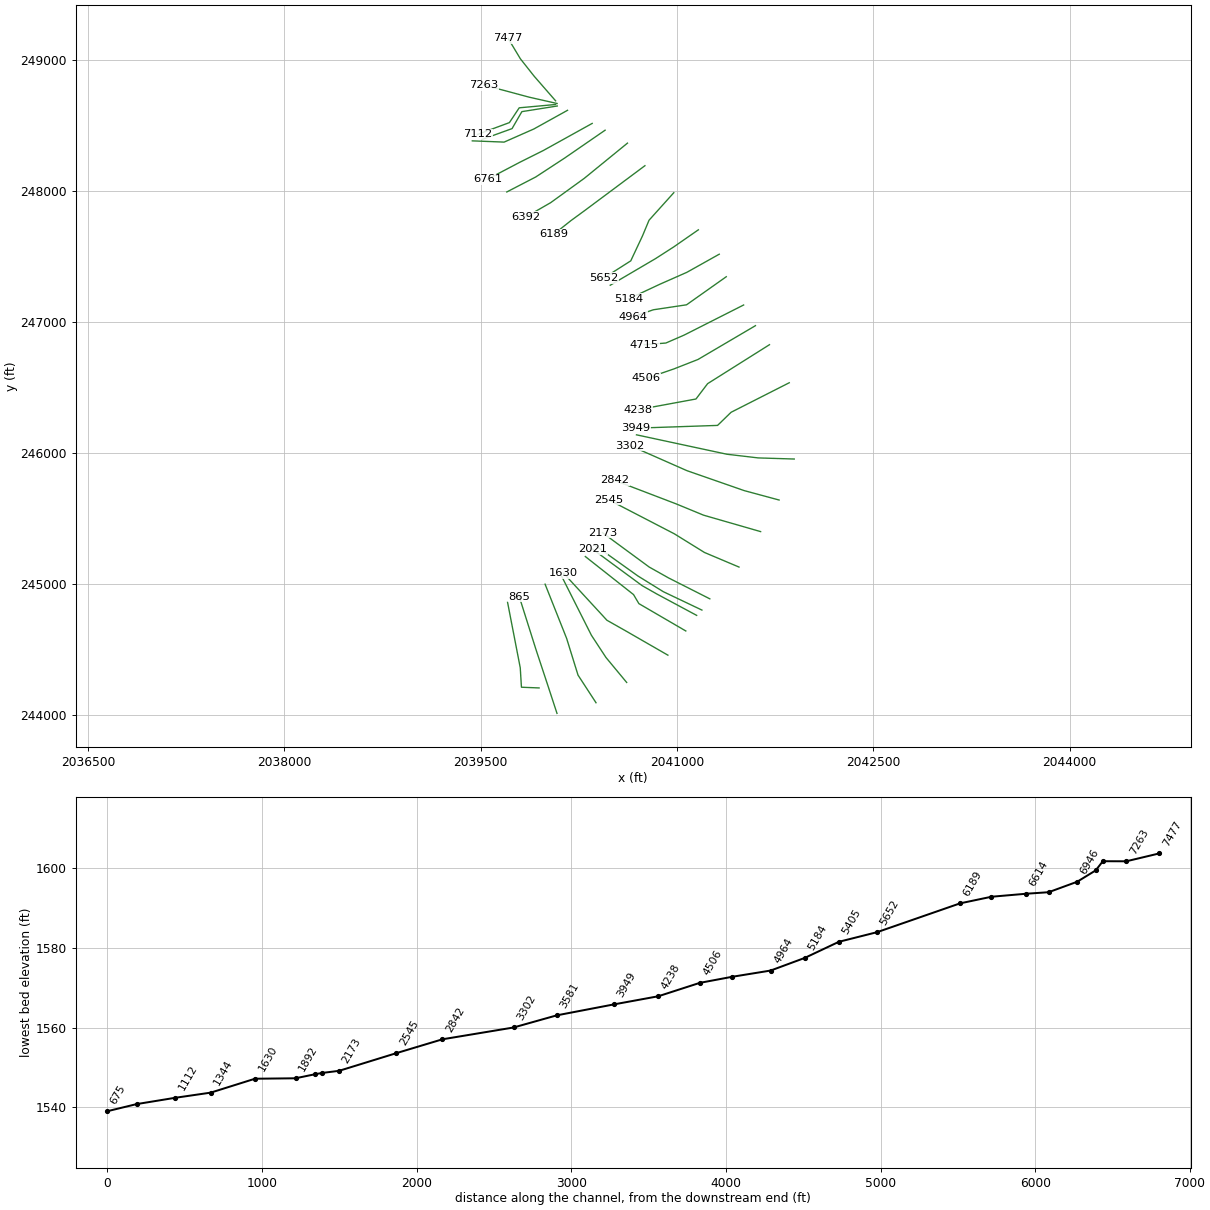
HEC-RAS study HNGRDCK_1.prj: HNGRDCK_1

--- HNGRDCK_1.g01 (geometry) --- (continued)

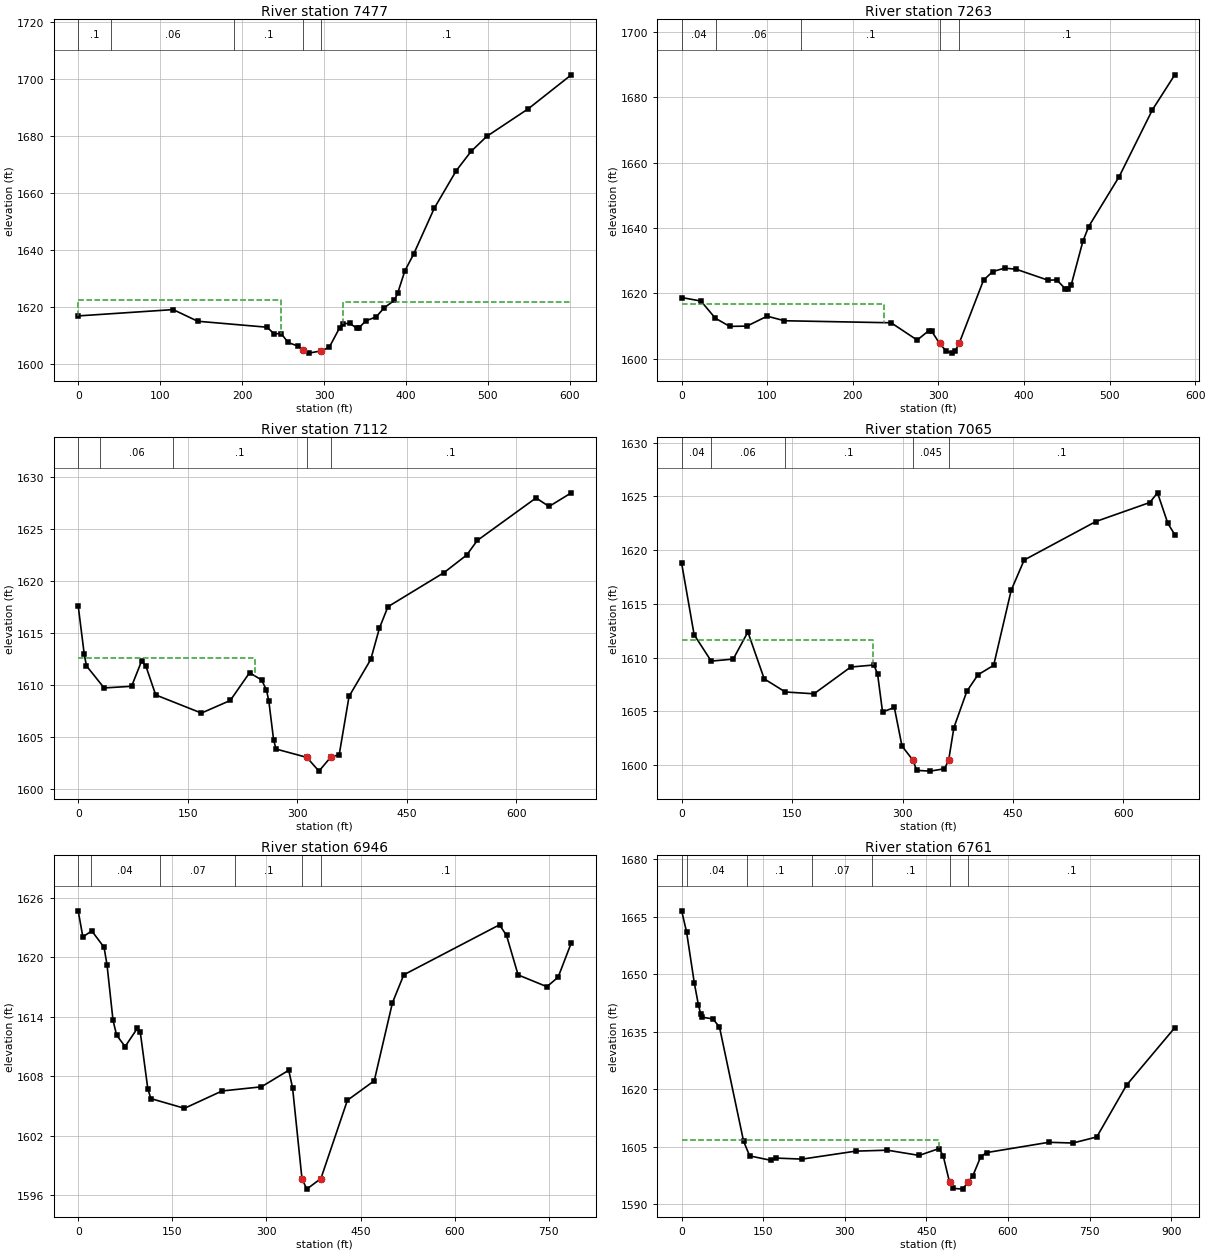
Type RM Length L Ch R = 1 ,7477    ,193.8,213.6,224.6
XS GIS Cut Line= 4
2040072.96557747248690.9204497542039909.08939154248878.933438257
2039803.64967502249012.3210314522039709.64318076249168.575069195
#Sta/Elev= 30
       0  1616.8   115.9 1619.02   145.8 1614.93   230.4 1612.83   239.1 1610.51
   247.8 1610.59   256.1 1607.47   267.8 1606.24   274.8 1604.65   281.3 1603.72
   296.7 1604.51   306.4 1605.78   318.9 1612.54   323.1 1614.05   331.5  1614.2
   339.8 1612.48   342.5 1612.62   351.3  1615.1   363.6 1616.45   373.3 1619.61
   385.8 1622.26     390 1624.89   398.6  1632.6   409.5  1638.6   434.6 1654.67
   461.4 1667.86   479.4  1674.6   498.5 1679.88   549.5 1689.65601.7894 1701.54
#Mann= 5 ,-1 , 0
       0      .1       0      40     .06       0     190      .1       0
   274.8    .045       0   296.7      .1       0
#XS Ineff= 2 , 0
          246.93 1622.38  322.92         1621.65
Permanent Ineff=
       F       F
Bank Sta=274.8,296.7
XS Rating Curve= 0 ,0
Exp/Cntr(USF)=0,0
Exp/Cntr=0.3,0.1

Type RM Length L Ch R = 1 ,7263    ,116.3,151.4,181.8
XS GIS Cut Line= 4
2040084.39879974248670.5947212672039870.97865063248718.868326423
2039686.77673622 248768.412289612039525.44126635248810.334104614
#Sta/Elev= 30
       0 1618.73    22.5 1617.67    39.3 1612.42    56.1 1609.92    76.3    1610
    99.9 1613.04     120 1611.64   244.8 1611.02   275.2 1605.73   288.5 1608.55
   292.3 1608.39  301.371604.699   309.3 1602.34   316.1 1601.74   319.5 1602.37
  324.221604.701   352.8 1624.08   363.5 1626.67   377.3 1627.72   390.8  1627.4
   428.2 1624.03   438.3 1624.14   448.5 1621.35   451.9 1621.23   455.3 1622.67
   468.9 1635.97   475.6 1640.42   511.3 1655.72   550.2 1676.18 576.253 1686.83
#Mann= 5 ,-1 , 0
       0     .04       0      40     .06       0     140      .1       0
  301.37    .045       0  324.22      .1       0
#XS Ineff= 2 , 0
             236 1616.87
Permanent Ineff=
       F       F
Bank Sta=301.37,324.22
XS Rating Curve= 0 ,0
Exp/Cntr(USF)=0,0
Exp/Cntr=0.5,0.3

Type RM Length L Ch R = 1 ,7112    ,44.1,46.6,50.7
XS GIS Cut Line= 4
2040072.96557747248662.972573084 2039794.7571688248637.565412476
2039719.80604501248524.5035477682039475.89730317248434.308127607
#Sta/Elev= 30
       0 1617.62     8.3 1612.96    11.3 1611.86    35.5 1609.74    73.1  1609.9
    86.8 1612.32    92.8 1611.81   106.1 1609.07   168.7 1607.33   208.2 1608.54
   234.6  1611.2     251 1610.51   257.6 1609.57   260.9 1608.52   267.5 1604.77
   270.8 1603.88     313 1603.08   329.6 1601.76   346.1 1603.13   357.3 1603.33
   370.8 1608.93   400.5 1612.47   412.4 1615.48     424 1617.53   500.9 1620.81
   531.8 1622.49   546.4 1623.89   626.8 1627.97   644.6 1627.15675.0665 1628.46
#Mann= 5 ,-1 , 0
       0     .04       0      30     .06       0     130      .1       0
     313    .045       0   346.1      .1       0
#XS Ineff= 2 , 0
          241.83 1612.62  360.03         1603.65
Permanent Ineff=
       F       F
Bank Sta=313,346.1
XS Rating Curve= 0 ,0
Exp/Cntr(USF)=0,0
Exp/Cntr=0.5,0.3

Type RM Length L Ch R = 1 ,7065    ,141,119.8,99.6
XS GIS Cut Line= 4
2040085.66915777248651.5393508112039815.08289729248608.347177776
 2039740.1317735248478.7706586722039508.92661196248394.927028664
#Sta/Elev= 30
       0 1618.76    16.9 1612.14    40.1 1609.68      70 1609.87    89.9 1612.39
   112.1 1608.03   140.8 1606.81   179.7 1606.64   229.6 1609.13     261 1609.32
     266  1608.5   272.8 1604.95   288.8 1605.37   299.2 1601.78  314.091600.468
   319.1 1599.52   337.6 1599.45   356.9 1599.67  362.561600.466   369.7  1603.5
   387.3 1606.88   402.4 1608.41   423.7 1609.29   447.5 1616.27   465.1 1619.08
   562.4 1622.66   635.7 1624.43   646.2 1625.33   660.2 1622.49669.6422 1621.44
#Mann= 5 ,-1 , 0
       0     .04       0      40     .06       0     140      .1       0
  314.09    .045       0  362.56      .1       0
#XS Ineff= 2 , 0
          260.04 1611.67  369.05          1600.9
Permanent Ineff=
       F       F
Bank Sta=314.09,362.56
XS Rating Curve= 0 ,0
Exp/Cntr(USF)=0,0
Exp/Cntr=0.5,0.3

Type RM Length L Ch R = 1 ,6946    ,182.9,184.3,185.7
XS GIS Cut Line= 4
2040164.06183764248618.6587872212039906.85354506248475.939551704
2039679.44377418248375.5655838682039436.35057083248384.975643352
#Sta/Elev= 30
       0  1624.7     7.4 1622.07    21.7 1622.67    41.2 1621.02    45.9 1619.27
    55.5 1613.65    61.2 1612.15    74.8 1610.99    94.1 1612.82      99 1612.43
     111 1606.71   115.9 1605.74   169.4 1604.76   229.3 1606.51     292 1606.93
   335.6  1608.6   341.7 1606.83  356.66 1597.67   364.3  1596.6  386.861597.667
   429.1 1605.57   471.9 1607.54   500.9 1615.42     519 1618.24   671.6 1623.29
   682.8 1622.21   701.2 1618.23   747.1 1617.04     765    1618786.0026 1621.47
#Mann= 6 ,-1 , 0
       0      .1       0      20     .04       0     130     .07       0
     250      .1       0  356.66    .045       0  386.86      .1       0
Bank Sta=356.66,386.86
XS Rating Curve= 0 ,0
Exp/Cntr(USF)=0,0
Exp/Cntr=0.3,0.1

Type RM Length L Ch R = 1 ,6761    ,144,147.1,150.7
XS GIS Cut Line= 4
2040352.26302733248518.2848193852039978.99733444248311.263510723
2039800.20620423248221.8679456182039552.40797114248091.695456081
#Sta/Elev= 30
       0 1666.48     9.1 1660.89    23.3 1647.62    30.8 1641.96      35  1639.6
    38.1 1638.77    57.4 1638.32    69.5 1636.22   113.8 1606.47     125 1602.64
   163.6  1601.5   173.2 1602.07   221.5  1601.8   320.1 1603.88   378.4 1604.12
   436.7 1602.76   473.1 1604.54   480.8 1602.69  492.491595.802   498.6  1594.2
   516.4 1593.98  526.781595.802   535.3 1597.44   549.9 1602.45   561.1 1603.51
   675.1 1606.18   719.2 1605.99   763.2 1607.57   817.9 1621.06906.6346 1636.03
#Mann= 7 ,-1 , 0
       0      .1       0      10     .04       0     120      .1       0
     240     .07       0     350      .1       0  492.49    .045       0
  526.78      .1       0
#XS Ineff= 2 , 0
          473.47 1606.83
Permanent Ineff=
       F       F
Bank Sta=492.49,526.78
XS Rating Curve= 0 ,0
Exp/Cntr(USF)=0,0
Exp/Cntr=0.3,0.1

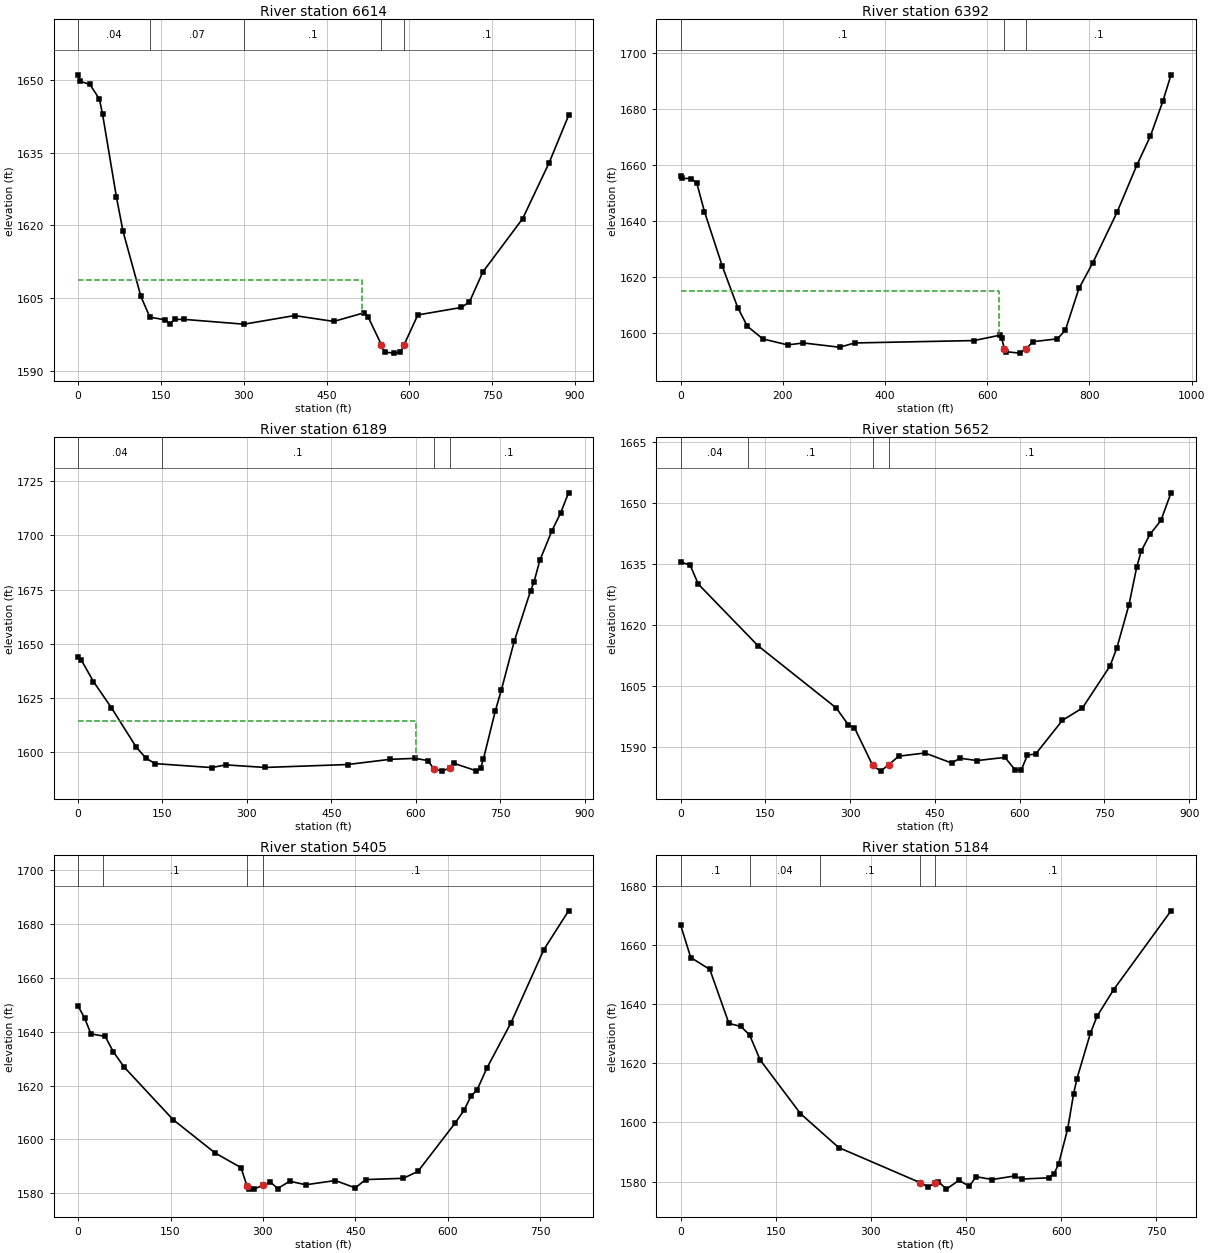
Type RM Length L Ch R = 1 ,6614    ,221.3,222.6,224.2
XS GIS Cut Line= 4
2040451.06865192248466.5294922192040143.67337542248254.803153815
2039920.96863429248108.947231803 2039699.8322364247994.458174739
#Sta/Elev= 30
       0  1651.1     3.9 1649.74    21.3 1649.13    38.6  1646.1    44.4 1642.94
    69.5 1625.84    81.5 1618.74   113.8 1605.32     130 1601.02   158.3 1600.46
   165.9 1599.61   174.9 1600.55   191.4 1600.57   300.6 1599.57   392.1 1601.35
   463.1 1600.14   517.6 1601.91   525.2 1601.12  549.611595.278   555.5  1593.8
   572.1 1593.59   583.9 1593.78  590.351595.278   615.4 1601.48   694.4 1603.03
     709 1604.19   733.3 1610.38   805.3 1621.38   853.3 1632.94888.4887  1642.7
#Mann= 5 ,-1 , 0
       0     .04       0     130     .07       0     300      .1       0
  549.61    .045       0  590.35      .1       0
#XS Ineff= 2 , 0
           513.51608.614
Permanent Ineff=
       F       F
Bank Sta=549.61,590.35
XS Rating Curve= 0 ,0
Exp/Cntr(USF)=0,0
Exp/Cntr=0.3,0.1

Type RM Length L Ch R = 1 ,6392    ,202.4,203,203.1
XS GIS Cut Line= 4
2040622.01806589 248367.723867632040291.09764068248097.968829071
2040035.45769135247912.9043258722039847.25650166247804.688641799
#Sta/Elev= 30
       0 1656.23     2.9 1655.24    21.3 1655.17      32 1653.46    46.9 1643.34
    81.9 1623.81   111.9 1609.12   130.8 1602.43   161.2 1597.91   209.7 1595.77
   240.4 1596.47   311.3 1594.94   340.7 1596.47   574.3 1597.33   624.1 1599.21
   628.2 1598.24  633.671594.379   636.3 1593.34   663.8 1592.84  676.681594.378
   688.9 1596.91   737.5 1597.95     753 1601.08   779.5 1615.93   806.7 1625.12
     854 1643.13     893 1660.05   919.2 1670.28   943.7  1682.8 959.629 1692.21
#Mann= 3 ,-1 , 0
       0      .1       0  633.67    .045       0  676.68      .1       0
#XS Ineff= 2 , 0
          622.751614.943
Permanent Ineff=
       F       F
Bank Sta=633.67,676.68
XS Rating Curve= 0 ,0
Exp/Cntr(USF)=0,0
Exp/Cntr=0.3,0.1

Type RM Length L Ch R = 1 ,6189    ,530.3,536.2,555.6
XS GIS Cut Line= 4
2040755.32724192248195.2061104122040287.96095419 247847.03390948
 2040189.1553296247774.8901200972040058.98284006247671.379465766
#Sta/Elev= 30
       0 1643.86     5.4  1642.6    27.3 1632.52      59 1620.52     103 1602.41
   120.7  1597.1   137.2 1594.64   237.2 1592.82   262.6 1594.06   332.1 1592.88
   478.7 1594.22   554.5 1596.63   598.7 1597.07   621.7 1596.03  631.811592.279
   646.7 1591.18   659.9  1592.6   668.7 1594.71   707.7  1591.3     715  1592.4
   720.2 1596.79   741.3    1619   751.9 1628.52   774.8 1651.01   804.1 1674.54
   809.8  1678.3   820.4 1688.47   841.7    1702   857.3 1710.35871.4512 1719.62
#Mann= 4 ,-1 , 0
       0     .04       0     150      .1       0  631.81    .045       0
   659.9      .1       0
#XS Ineff= 2 , 0
             6001614.308
Permanent Ineff=
       F       F
Bank Sta=631.81,659.9
XS Rating Curve= 0 ,0
Exp/Cntr(USF)=0,0
Exp/Cntr=0.3,0.1

Type RM Length L Ch R = 1 ,5652    ,261,247.3,234.7
XS GIS Cut Line= 5
2040976.02974421247988.9159619282040786.88754857247778.601132446
2040736.07322735247657.2113650942040647.14816522247468.069169452
2040441.06786251247336.798839641
#Sta/Elev= 30
       0 1635.42      17 1634.66    31.5 1629.96   137.2 1614.79   275.4 1599.51
   297.1  1595.3   307.7 1594.64  340.011585.347     354 1583.95   368.2  1585.5
     386 1587.63   432.6 1588.41   479.7 1585.94   494.2 1587.13   524.9 1586.55
   573.9 1587.33   592.1 1584.25     603 1584.28   613.8 1587.91   628.2 1588.14
   675.6 1596.44   711.1 1599.49   759.9 1609.82   772.1 1614.31   793.5 1624.94
   807.1 1634.13   814.9 1638.04   830.4 1642.18   849.9 1645.63867.7928 1652.43
#Mann= 4 ,-1 , 0
       0     .04       0     120      .1       0  340.01    .045       0
   368.2      .1       0
Bank Sta=340.01,368.2
XS Rating Curve= 0 ,0
Exp/Cntr(USF)=0,0
Exp/Cntr=0.3,0.1

Type RM Length L Ch R = 1 ,5405    ,222.6,220.9,214.9
XS GIS Cut Line= 4
2041163.76043093247705.2026684652040974.61823529247573.932338654
2040836.29036086247485.007276524 2040490.4706748247281.749991656
#Sta/Elev= 30
       0 1649.54    10.7 1645.04    20.8  1639.2    43.9 1638.27    57.3 1632.52
    74.6 1626.91   153.9 1607.39   222.2 1594.98   264.3 1589.52  274.02 1582.76
   277.1 1581.69   284.9 1581.53   300.5 1582.99   312.2 1584.12   323.9 1581.75
   343.4 1584.47   369.4 1583.15   417.4 1584.72   449.8 1581.99   466.5 1585.08
   527.5 1585.54   551.4  1588.1   611.3 1605.94   626.3 1610.85   637.6 1616.17
   647.2 1618.31   663.4 1626.55   702.3 1643.29   755.7  1670.5795.8065  1684.9
#Mann= 4 ,-1 , 0
       0     .04       0      40      .1       0  274.02    .045       0
   300.5      .1       0
Bank Sta=274.02,300.5
XS Rating Curve= 0 ,0
Exp/Cntr(USF)=0,0
Exp/Cntr=0.3,0.1

Type RM Length L Ch R = 1 ,5184    ,226.9,220.5,216.4
XS GIS Cut Line= 4
2041323.26093919247518.8834906692041076.24687772247380.555616245
2040871.57808393247290.2190451922040630.21005815247177.298331376
#Sta/Elev= 30
       0 1666.78    16.1 1655.69    46.2 1651.68    76.3 1633.46    95.1 1632.41
   108.8 1629.58   125.6 1621.09   189.1 1602.99   249.3 1591.53   377.9 1579.66
   390.7 1578.19   401.5 1579.62   406.7 1580.02   419.1 1577.48     439 1580.45
   455.3 1578.44     466 1581.68   491.3 1580.72   527.2 1581.94     538 1580.88
   580.3  1581.3   588.8  1582.6     596 1585.92   610.5 1597.95   619.7 1609.63
     625  1614.8   646.2 1630.11   656.7 1635.86   682.9 1644.86773.3036 1671.46
#Mann= 5 ,-1 , 0
       0      .1       0     110     .04       0     220      .1       0
   377.9    .045       0   401.5      .1       0
Bank Sta=377.9,401.5
XS Rating Curve= 0 ,0
Exp/Cntr(USF)=0,0
Exp/Cntr=0.3,0.1

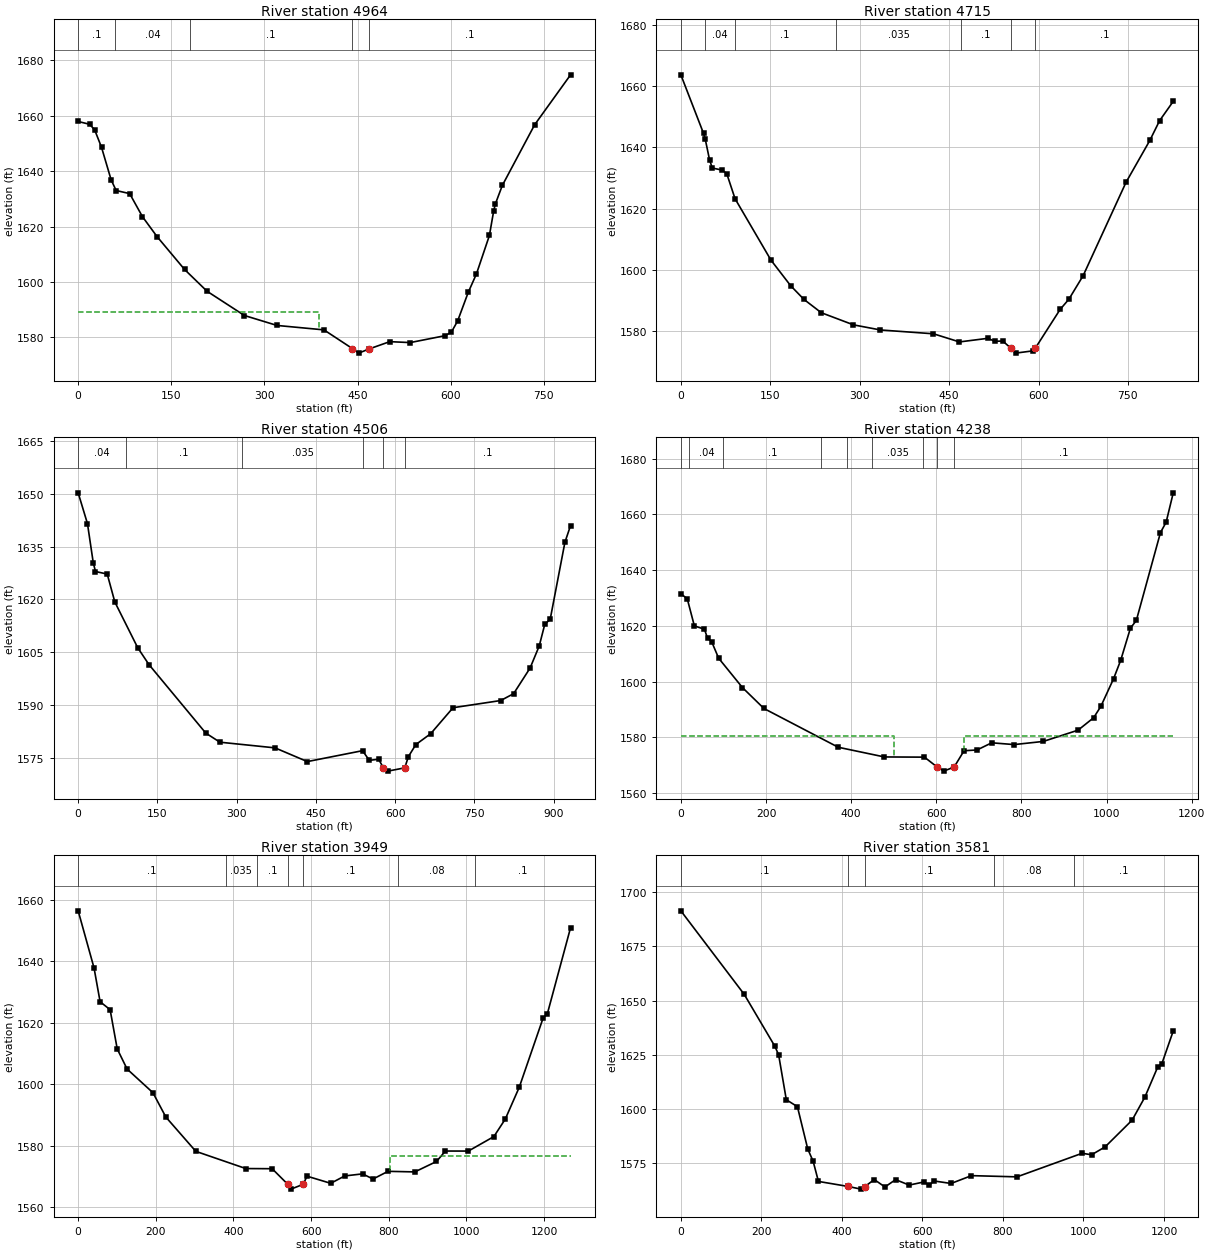
Type RM Length L Ch R = 1 ,4964    ,240.1,248.2,258.8
XS GIS Cut Line= 4
2041376.89827825  247346.67940212041073.42385987 247132.13004585
2040819.64140764247094.0674972462040663.98200792247040.397725386
#Sta/Elev= 30
       01657.964  18.6481656.949  26.6841654.878  37.6281648.635  53.1081636.875
  61.1661633.035  82.9351631.922 103.5351623.589 127.0731616.382  171.33 1604.53
 207.4911596.667  267.761587.899 320.2211584.309 395.824 1582.71   441.51575.972
 451.7481574.312   468.21575.793 501.7391578.457 534.686 1578.12 591.0841580.625
 601.0371581.914 610.9891585.882 628.277 1596.33 641.4261602.952 662.2481616.802
 669.1891625.757 672.0431628.319  683.071634.884 735.1261656.794 792.9291674.818
#Mann= 5 ,-1 , 0
       0      .1       0      60     .04       0     180      .1       0
   441.5    .045       0   468.2      .1       0
#XS Ineff= 2 , 0
          387.93 1589.05
Permanent Ineff=
       F       F
Bank Sta=441.5,468.2
XS Rating Curve= 0 ,0
Exp/Cntr(USF)=0,0
Exp/Cntr=0.3,0.1

Type RM Length L Ch R = 1 ,4715    ,211,210,208.8
XS GIS Cut Line= 4
2041509.58011699247130.7185369272041055.07424388246900.642582528
2040915.33486053246839.947698852 2040751.5998255246827.244118547
#Sta/Elev= 30
       0 1663.73    38.1 1644.55    40.8  1642.8    48.1 1635.97    52.7 1633.26
    69.8 1632.57    77.2 1631.31    90.9 1623.23   151.1 1603.17   184.2 1594.79
   206.5 1590.31   235.6 1585.96   289.6 1581.99   334.9 1580.32   423.8 1579.07
   467.3 1576.41     515 1577.59   526.7 1576.61     540 1576.71  553.481574.383
   561.5 1572.75   590.1 1573.48  594.661574.384   636.2 1587.03   650.9 1590.37
   674.8 1598.06   746.8  1628.6   786.7 1642.28   803.1 1648.75826.0003 1655.06
#Mann= 7 ,-1 , 0
       0      .1       0      40     .04       0      90      .1       0
     260    .035       0     470      .1       0  553.48    .045       0
  594.66      .1       0
Bank Sta=553.48,594.66
XS Rating Curve= 0 ,0
Exp/Cntr(USF)=0,0
Exp/Cntr=0.3,0.1

Type RM Length L Ch R = 1 ,4506    ,249.1,268,281.7
XS GIS Cut Line= 4
2041599.91668804246972.6295375852041160.93741308246714.323404731
2040977.44125313246642.336449674 2040764.3034058246568.937985694
#Sta/Elev= 30
       0  1650.3    17.6 1641.55    28.6  1630.4    32.8 1627.94      55 1627.22
    69.4 1619.28   112.7 1606.29   134.1 1601.47   241.5 1582.03   268.3 1579.44
   372.6 1577.83   433.7 1573.93   538.2 1577.03     551 1574.28   568.6  1574.6
   577.71572.152     586 1571.22  618.07 1572.15     625 1575.36   639.1 1578.77
   667.2 1581.86   709.5 1589.24   799.7 1591.28   824.1 1593.23   855.3 1600.52
   872.6  1606.8     883 1612.89   893.4 1614.42   921.2 1636.25931.8712    1641
#Mann= 6 ,-1 , 0
       0     .04       0      90      .1       0     310    .035       0
  539.34      .1       0   577.7    .045       0  618.07      .1       0
Bank Sta=577.7,618.07
XS Rating Curve= 0 ,0
Exp/Cntr(USF)=0,0
Exp/Cntr=0.3,0.1

Type RM Length L Ch R = 1 ,4238    ,289.9,288.1,280.9
XS GIS Cut Line= 4
2041707.19136617246827.2441185472041234.33587706246529.415735858
2041145.41081493246412.2604952742040702.19701321246330.392977758
#Sta/Elev= 30
       0 1631.57    15.1 1629.69    31.7 1620.01    55.5 1618.78    62.7 1615.54
    72.2 1614.39    88.8 1608.39   144.7 1597.85   195.1 1590.35   369.7 1576.43
   478.1 1572.95   572.2 1572.88  601.931569.338   617.5 1567.86  641.991569.337
   665.2 1575.18   695.7 1575.45   730.2 1578.03   782.9 1577.39   851.3 1578.52
   933.1 1582.57   969.6 1587.03   986.5 1591.09  1016.5 1601.05  1033.2 1607.67
    1056 1619.18  1069.9 1621.95  1126.6 1653.51  1139.9 1657.221156.626 1667.77
#Mann= 9 ,-1 , 0
       0     .06       0      20     .04       0     100      .1       0
     330    .035       0     390      .1       0     450    .035       0
  568.83      .1       0  601.93    .045       0  641.99      .1       0
#XS Ineff= 2 , 0
             500 1580.48  664.31         1580.48
Permanent Ineff=
       F       F
Bank Sta=601.93,641.99
XS Rating Curve= 0 ,0
Exp/Cntr(USF)=0,0
Exp/Cntr=0.3,0.1

Type RM Length L Ch R = 1 ,3949    ,386.8,368.2,339.8
XS GIS Cut Line= 4
2041858.22282089246536.4732804722041413.59751025 246310.63185284
2041310.55735889246210.4147193282040685.25890613246189.242085488
#Sta/Elev= 30
       0 1656.33    40.9 1637.75    56.5 1626.76    82.3 1624.18   100.6 1611.41
     126 1604.87   192.6 1597.17   225.8 1589.26     303  1578.1   431.8  1572.5
   499.6 1572.45  539.771567.383   548.2 1565.81  579.511567.382   589.4 1570.02
   650.4  1567.7   686.5  1570.1   732.4 1570.77   759.4  1569.1   798.1  1571.6
     867 1571.41   922.8  1574.8   945.8  1578.2  1004.9 1578.19  1070.6  1582.9
  1100.1 1588.62    1136 1598.96  1197.7 1621.57  1208.4 1622.88 1268.09 1650.84
#Mann= 7 ,-1 , 0
       0      .1       0     380    .035       0     460      .1       0
  539.77    .045       0  579.51      .1       0  822.43     .08       0
 1022.43      .1       0
#XS Ineff= 2 , 0
                          802.71         1576.47
Permanent Ineff=
       F       F
Bank Sta=539.77,579.51
XS Rating Curve= 0 ,0
Exp/Cntr(USF)=0,0
Exp/Cntr=0.3,0.1

Type RM Length L Ch R = 1 ,3581    ,284.9,279.3,272.2
XS GIS Cut Line= 4
2041896.33356181245953.5200953972041621.08932188245961.989148934
2041381.13280502245990.2193273882040690.90494182246138.427764271
#Sta/Elev= 30
       0 1691.41   157.4 1652.88   233.3    1629   242.8 1625.04   261.9  1604.3
   289.5 1601.09   315.2 1581.55   328.5 1575.94   341.7 1566.62   415.3 1564.31
   447.4 1563.07   456.4 1564.18   480.4 1567.48   506.9 1564.06   533.3 1567.45
   567.1 1564.94     604 1566.38   617.4 1564.81   627.5 1566.87   671.1 1565.68
   721.8 1569.29   834.8 1568.73   996.6  1579.6  1020.1 1578.91  1053.7 1582.55
  1120.8 1594.89  1152.5 1605.52  1184.5 1619.45  1194.6 1620.891222.946 1636.01
#Mann= 5 ,-1 , 0
       0      .1       0   415.3    .045       0   456.4      .1       0
  776.99     .08       0  976.99      .1       0
Bank Sta=415.3,456.4
XS Rating Curve= 0 ,0
Exp/Cntr(USF)=0,0
Exp/Cntr=0.3,0.1

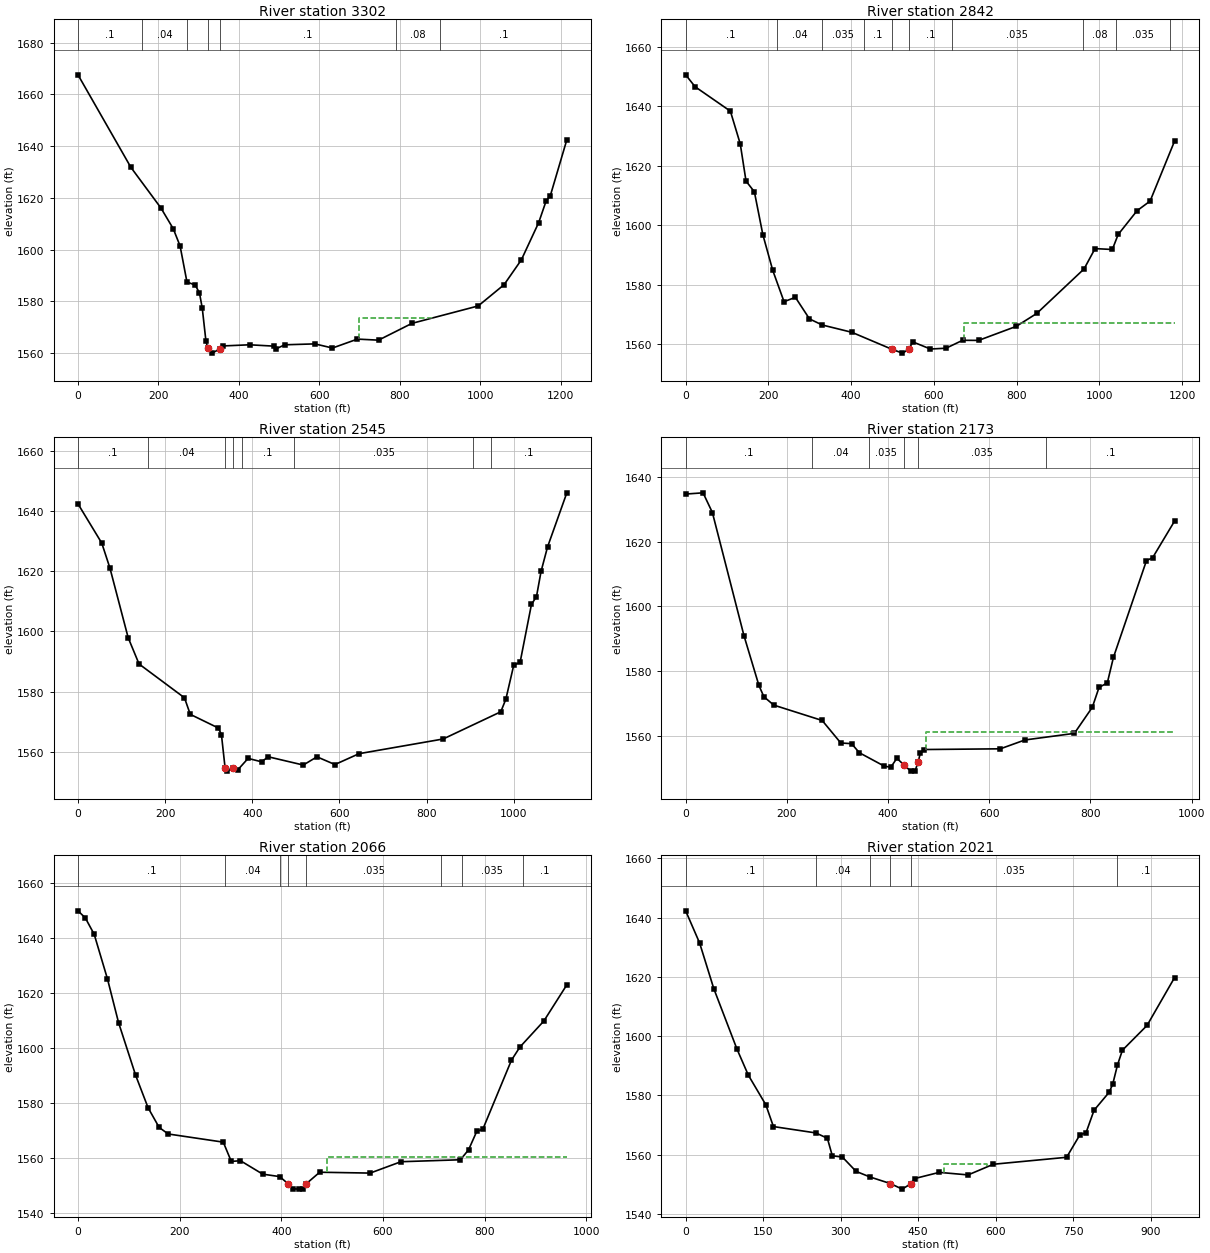
Type RM Length L Ch R = 1 ,3302    ,457.2,459.7,460.4
XS GIS Cut Line= 4
2041780.58983015245640.1651145592041513.81464376245712.152069616
2041076.24687772245864.5950332672040641.50212953246056.560246754
#Sta/Elev= 30
       0 1667.54   131.5 1631.79   206.2 1616.08   236.8 1608.07   253.8  1601.4
   270.8 1587.53   291.5 1586.28   301.9 1583.28   308.9 1577.38   318.1 1564.53
  322.461562.054   333.6 1560.02     354 1561.79     361  1562.8   426.4 1563.24
   486.1 1562.73     493 1561.71   513.6 1563.24   588.7 1563.59   632.5 1561.99
   694.5 1565.44   746.9 1565.03   830.2 1571.53   994.7 1578.25  1058.9 1586.45
  1101.9 1596.05    1145 1610.45  1163.6 1618.87  1173.9 1620.84 1214.92 1642.44
#Mann= 7 ,-1 , 0
       0      .1       0     160     .04       0     270      .1       0
  322.46    .045       0     354      .1       0  789.68     .08       0
  899.68      .1       0
#XS Ineff= 1 ,-1
698.2944887.1086 1573.58
Permanent Ineff=
       T
Bank Sta=322.46,354
XS Rating Curve= 0 ,0
Exp/Cntr(USF)=0,0
Exp/Cntr=0.3,0.1

Type RM Length L Ch R = 1 ,2842    ,294.2,297.3,297.8
XS GIS Cut Line= 4
2041639.43893788245398.7970887772041203.28268076245524.421382897
 2040994.3793602245610.5234271822040525.75839787245789.785060364
#Sta/Elev= 30
       0 1650.59    22.8 1646.59   108.1 1638.38     132 1627.36   145.9 1614.88
   166.1 1611.28   186.6 1596.86   210.5 1584.87   237.8 1574.35   265.2 1575.81
   299.3 1568.56     330 1566.52   401.7 1564.06  498.971558.333   523.9 1557.06
  539.641558.335   548.7 1560.86   591.6 1558.44   629.3 1558.71   669.4 1561.37
   708.1 1561.34     799 1566.05   848.6 1570.39     963 1585.36   989.5 1592.19
  1031.3 1591.89  1045.4 1596.93    1091 1604.91  1122.6 1608.161181.576 1628.27
#Mann= 10 ,-1 , 0
       0      .1       0     220     .04       0     330    .035       0
     430      .1       0  498.97    .045       0  539.64      .1       0
  643.89    .035       0  959.84     .08       0 1039.84    .035       0
 1169.84      .1       0
#XS Ineff= 2 , 0
                           671.8         1567.14
Permanent Ineff=
       F       F
Bank Sta=498.97,539.64
XS Rating Curve= 0 ,0
Exp/Cntr(USF)=0,0
Exp/Cntr=0.3,0.1

Type RM Length L Ch R = 1 ,2545    ,368.1,371.6,375.3
XS GIS Cut Line= 4
2041474.29239392245127.7873756192041210.34022538245239.296580512
2040980.26427098245381.8589817052040479.17860342245641.576623481
#Sta/Elev= 30
       0 1642.34    54.6 1629.31    73.4 1620.98   115.1 1597.92   140.1 1589.17
   244.3 1577.95   257.6 1572.45     322 1567.91   329.1 1565.75  337.61 1554.54
     341 1553.59   355.5 1554.58   367.2  1554.1   390.3 1557.82   421.1 1556.69
   436.6 1558.35   516.9 1555.61   548.3 1558.34   589.5 1555.78     645 1559.39
   837.8 1564.26   970.1  1573.3   981.7 1577.48   999.7 1588.71  1014.5 1589.79
  1040.4 1608.93    1052 1611.57  1062.5 1619.92  1077.3 1628.011121.597 1646.01
#Mann= 8 ,-1 , 0
       0      .1       0     160     .04       0  337.61    .045       0
   355.5     .04       0  376.54      .1       0  496.54    .035       0
   907.2     .08       0   947.2      .1       0
Bank Sta=337.61,355.5
XS Rating Curve= 0 ,0
Exp/Cntr(USF)=0,0
Exp/Cntr=0.3,0.1

Type RM Length L Ch R = 1 ,2173    ,108.7,107.4,105.9
XS GIS Cut Line= 4
2041251.27398413244885.0078409152040936.50749437 245044.50834918
2040788.29905749245127.7873756192040431.18730005245390.328035241
#Sta/Elev= 30
       0  1634.7    34.4 1635.08    52.8    1629   115.3 1590.94   144.8 1575.59
   154.6 1572.11   174.1 1569.53   269.8 1564.78   306.6 1557.83   327.9 1557.62
   343.3 1554.82     392 1550.72   405.3 1550.32   417.4  1553.1   430.6 1551.18
   444.7 1549.14   453.5  1549.3   459.8 1552.04   463.5 1554.63   471.1 1555.81
   621.9 1556.03   670.4 1558.76   768.2  1560.8   803.7 1568.86     817 1575.01
   833.3 1576.37   845.5 1584.31   910.7 1614.14   922.9 1615.05966.1089 1626.32
#Mann= 6 ,-1 , 0
       0      .1       0     250     .04       0  362.87    .035       0
   430.6    .045       0   459.8    .035       0  712.87      .1       0
#XS Ineff= 2 , 0
                             475         1561.23
Permanent Ineff=
       F       F
Bank Sta=430.6,459.8
XS Rating Curve= 0 ,0
Exp/Cntr(USF)=0,0
Exp/Cntr=0.5,0.3

Type RM Length L Ch R = 1 ,2066    ,42.7,44.6,45
XS GIS Cut Line= 4
2041190.90648911244799.0417352272040895.81099525244939.629682776
2040702.32857239245059.3382321732040371.04212173245295.971411216
#Sta/Elev= 30
       0 1649.75    14.4 1647.18    31.9 1641.21      58    1625    79.8 1609.13
   113.5 1589.94   137.9 1578.18   159.7 1571.03   177.5 1568.66   285.8 1565.69
   301.5 1558.69   319.6 1558.94   363.4 1554.06   396.8 1553.17   413.5 1550.53
   423.3 1548.75   434.9 1548.62   442.6 1548.83   449.2  1550.6   475.4 1554.76
   574.7 1554.45   635.2 1558.58   752.1 1559.29   768.2 1562.89   784.3 1569.59
   796.4 1570.44   852.6 1595.48   869.2 1600.24   916.3 1609.71   961.5 1622.85
#Mann= 8 ,-1 , 0
       0      .1       0     290     .04       0  396.87    .035       0
   413.5    .045       0   449.2    .035       0  714.39      .1       0
  754.39    .035       0  874.39      .1       0
#XS Ineff= 2 , 0
          407.59  1550.8  490.11         1560.24
Permanent Ineff=
       F       F
Bank Sta=413.5,449.2
XS Rating Curve= 0 ,0
Exp/Cntr(USF)=0,0
Exp/Cntr=0.5,0.3

Type RM Length L Ch R = 1 ,2021    ,139.8,129.2,108.9
XS GIS Cut Line= 4
2041150.53965269244758.6748988022040847.09239956244921.534204378
2040734.34364955244985.5643587072040354.33860321245265.348293928
#Sta/Elev= 30
       0  1642.3      27 1631.44    54.5 1615.99    99.2 1595.64   121.3 1586.79
   155.1  1576.8   169.8 1569.44   251.9 1567.29   274.2 1565.49   283.8 1559.56
   303.2 1559.15   329.8  1554.3   356.6 1552.42   396.3 1550.18     419 1548.31
   435.8 1550.13   443.1 1551.88   490.7 1553.97   546.5 1553.11   595.4 1556.71
   737.1 1559.06   762.9 1566.66   774.7 1567.34   790.2 1574.94   819.3 1580.99
   826.3 1583.71   835.5 1590.19   845.1 1595.22   892.8  1603.6   945.9 1619.71
#Mann= 6 ,-1 , 0
       0      .1       0   251.9     .04       0   356.6    .035       0
   396.3    .045       0   435.8    .035       0   835.5      .1       0
#XS Ineff= 3 ,-1
       0  390.42 1550.24  443.78  475.26 1550.37     500  583.21 1556.68
Permanent Ineff=
       F       F       F
Bank Sta=396.3,435.8
XS Rating Curve= 0 ,0
Exp/Cntr(USF)=0,0
Exp/Cntr=0.5,0.3

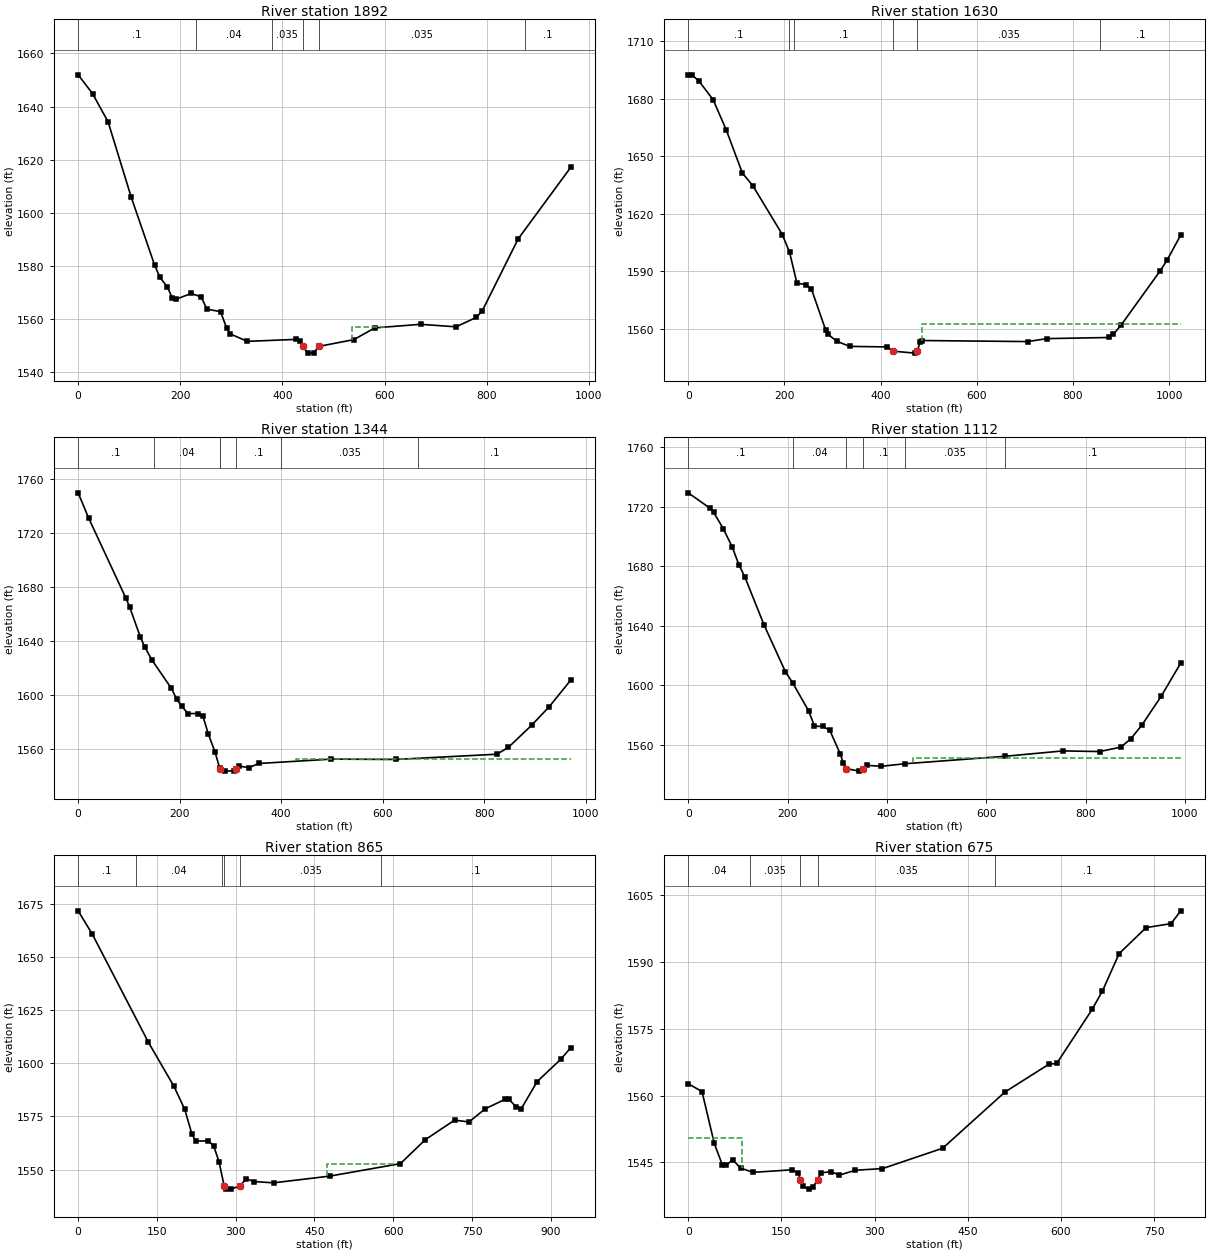
Type RM Length L Ch R = 1 ,1892    ,248.2,262,276.2
XS GIS Cut Line= 4
2041067.77782418244639.4052883662040709.25455782244848.308608925
2040668.32079906244917.4725461372040299.91697024245208.243384213
#Sta/Elev= 30
       0 1651.97    28.2 1644.89    58.6 1634.28   104.1 1605.82   149.7  1580.4
     160 1575.78   174.9 1572.12   183.9 1568.19   192.5 1567.61   221.3 1569.71
   240.8 1568.43   252.2 1563.82   278.8 1562.87   290.9 1556.63   297.8  1554.5
   331.3  1551.7     427 1552.44   434.8 1551.81   439.51549.787   449.9 1547.27
   461.3 1547.42  471.041549.788   539.9 1552.36   581.1 1556.77   670.5 1558.11
     740 1557.17   779.7  1560.7   791.4 1563.19   861.7 1590.24964.6428 1617.17
#Mann= 6 ,-1 , 0
       0      .1       0     230     .04       0     380    .035       0
   439.5    .045       0  471.04    .035       0  875.31      .1       0
#XS Ineff= 1 ,-1
535.3785606.4503 1557.03
Permanent Ineff=
       T
Bank Sta=439.5,471.04
XS Rating Curve= 0 ,0
Exp/Cntr(USF)=0,0
Exp/Cntr=0.3,0.1

Type RM Length L Ch R = 1 ,1630    ,293.1,286.2,271.3
XS GIS Cut Line= 4
2040930.86145868244454.4976194932040604.80289754244642.228306211
2040465.06351419244721.2728058822040134.77042628245079.796072248
#Sta/Elev= 30
       0 1692.47     7.9 1692.33    21.5 1689.47    51.8 1679.47      79 1663.74
   112.6 1641.17   134.3 1634.58   195.7 1609.08   210.8 1599.73     226 1583.78
   244.8 1582.83   256.3 1580.58   285.6 1559.37   290.3 1556.99   309.6 1553.29
   335.8 1550.68     413  1550.4     426  1548.2   470.8 1547.16  475.82  1548.2
   482.9 1553.22   486.7 1553.74   705.8 1553.19   745.9 1554.74   874.3 1555.32
   884.2 1557.02   900.4  1561.9   980.9 1589.94   995.6 1595.611024.263 1608.89
#Mann= 6 ,-1 , 0
       0      .1       0     210     .04       0     220      .1       0
     426    .045       0  475.82    .035       0  856.79      .1       0
#XS Ineff= 2 , 0
                           486.7         1562.54
Permanent Ineff=
       F       F
Bank Sta=426,475.82
XS Rating Curve= 0 ,0
Exp/Cntr(USF)=0,0
Exp/Cntr=0.3,0.1

Type RM Length L Ch R = 1 ,1344    ,239.8,231.9,225.2
XS GIS Cut Line= 4
2040615.89941007244245.857625701 2040457.1288591 244437.54402261
2040346.76396391244605.995704743 2040112.4805899245070.690000281
#Sta/Elev= 30
       0  1749.5    20.4 1731.03    94.3 1671.37   101.3  1665.2   122.6 1642.75
   131.2 1635.51   145.6 1625.72   183.6 1604.95   193.8 1597.14   203.8 1591.72
   216.4 1586.28   236.5  1586.2   245.8 1584.36   256.7 1570.88   269.9 1557.57
   278.9 1545.93  279.851545.321   288.4 1543.67   307.3 1543.94  311.631545.324
     317 1547.36   336.6 1546.31   356.2 1549.33   498.8 1552.54   625.4  1552.3
   825.1 1556.18   847.6 1561.16   894.1 1577.76   928.3 1591.32970.7001 1610.96
#Mann= 7 ,-1 , 0
       0      .1       0     150     .04       0   278.9      .1       0
  279.85    .045       0  311.63      .1       0   398.9    .035       0
  670.29      .1       0
#XS Ineff= 2 , 0
                          429.98         1552.89
Permanent Ineff=
       F       F
Bank Sta=279.85,311.63
XS Rating Curve= 0 ,0
Exp/Cntr(USF)=0,0
Exp/Cntr=0.3,0.1

Type RM Length L Ch R = 1 ,1112    ,246.3,247.3,247.3
XS GIS Cut Line= 4
2040381.61603607244090.9595271882040244.14397364244302.008186412
2040157.01379323244582.7609899662039992.43456356244997.113403488
#Sta/Elev= 30
       0 1729.46    43.3 1719.25    50.9 1716.47    70.5 1705.38    88.4  1693.2
   101.8 1681.25   113.6  1673.2   152.7 1640.62   195.8 1609.06   210.3 1601.73
   242.8  1582.6   254.2 1572.57   271.4  1572.4   285.1 1569.75   305.7 1554.21
   312.6 1547.49  318.531544.077   343.8 1542.36  351.621544.078   360.7 1546.25
   388.2 1545.59   436.3 1547.32     638 1552.35   754.5 1555.95   828.6 1555.53
     871  1558.5   890.9 1564.06   913.3 1573.29   952.2 1592.68991.6765 1615.09
#Mann= 6 ,-1 , 0
       0      .1       0   210.3     .04       0  318.53    .045       0
  351.62      .1       0   436.3    .035       0     638      .1       0
#XS Ineff= 2 , 0
                          452.26         1550.87
Permanent Ineff=
       F       F
Bank Sta=318.53,351.62
XS Rating Curve= 0 ,0
Exp/Cntr(USF)=0,0
Exp/Cntr=0.3,0.1

Type RM Length L Ch R = 1 ,865     ,196.6,189.9,184.2
XS GIS Cut Line= 4
2040083.43719643244009.6380254692040004.05192095244251.666304395
2039924.66664546 244491.758357092039794.93948795244902.238318149
#Sta/Elev= 30
       0 1671.65    26.9 1660.68   133.9 1609.77   182.3 1589.16     203 1578.28
   216.3 1566.94   223.7 1563.36   247.9 1563.48   257.9 1561.21   268.3 1553.64
  278.011542.317   282.4 1540.91   291.6 1540.79   308.11542.321   320.4 1545.71
   334.3 1544.36   372.3 1543.75   479.4 1546.92   613.7 1552.78   661.4 1564.09
   716.9 1573.23   744.4 1572.38   775.4  1578.6   813.6 1583.07   820.1 1583.18
     834 1579.42   844.2  1578.7     874 1591.33   919.3  1601.9938.0823 1607.28
#Mann= 6 ,-1 , 0
       0      .1       0     110     .04       0  274.71    .035       0
  278.01    .045       0   308.1    .035       0  577.59      .1       0
#XS Ineff= 1 ,-1
 473.825604.3896 1552.67
Permanent Ineff=
       T
Bank Sta=278.01,308.1
XS Rating Curve= 0 ,0
Exp/Cntr(USF)=0,0
Exp/Cntr=0.3,0.1

Type RM Length L Ch R = 1 ,675     ,234.5,236.3,237.2
XS GIS Cut Line= 4
2039946.80584343244204.0455947242039811.78138007244209.465291377
2039802.68439288244358.1587471222039705.87308131244857.705114826
#Sta/Elev= 30
       0 1562.66    22.2  1560.9    41.9 1549.28      55 1544.42    60.9 1544.32
    71.4 1545.58    84.5 1543.72   104.2 1542.77   167.7 1543.34   177.5 1542.58
  180.271541.119     184  1539.6   193.9    1539   200.5 1539.44  208.481541.116
   213.6 1542.66   230.1 1542.93   243.2 1542.14   269.2 1543.24   312.7 1543.61
   409.6 1548.18   509.9  1560.8   580.1    1567   593.4 1567.25   650.2 1579.34
   666.9  1583.5   693.7 1591.88   737.1 1597.71   777.2 1598.61792.9455 1601.48
#Mann= 5 ,-1 , 0
       0     .04       0     100    .035       0  180.27    .045       0
  208.48    .035       0   494.1      .1       0
#XS Ineff= 2 , 0
           85.96 1550.55
Permanent Ineff=
       F       F
Bank Sta=180.27,208.48
XS Rating Curve= 0 ,0
Exp/Cntr(USF)=0,0
Exp/Cntr=0.3,0.1