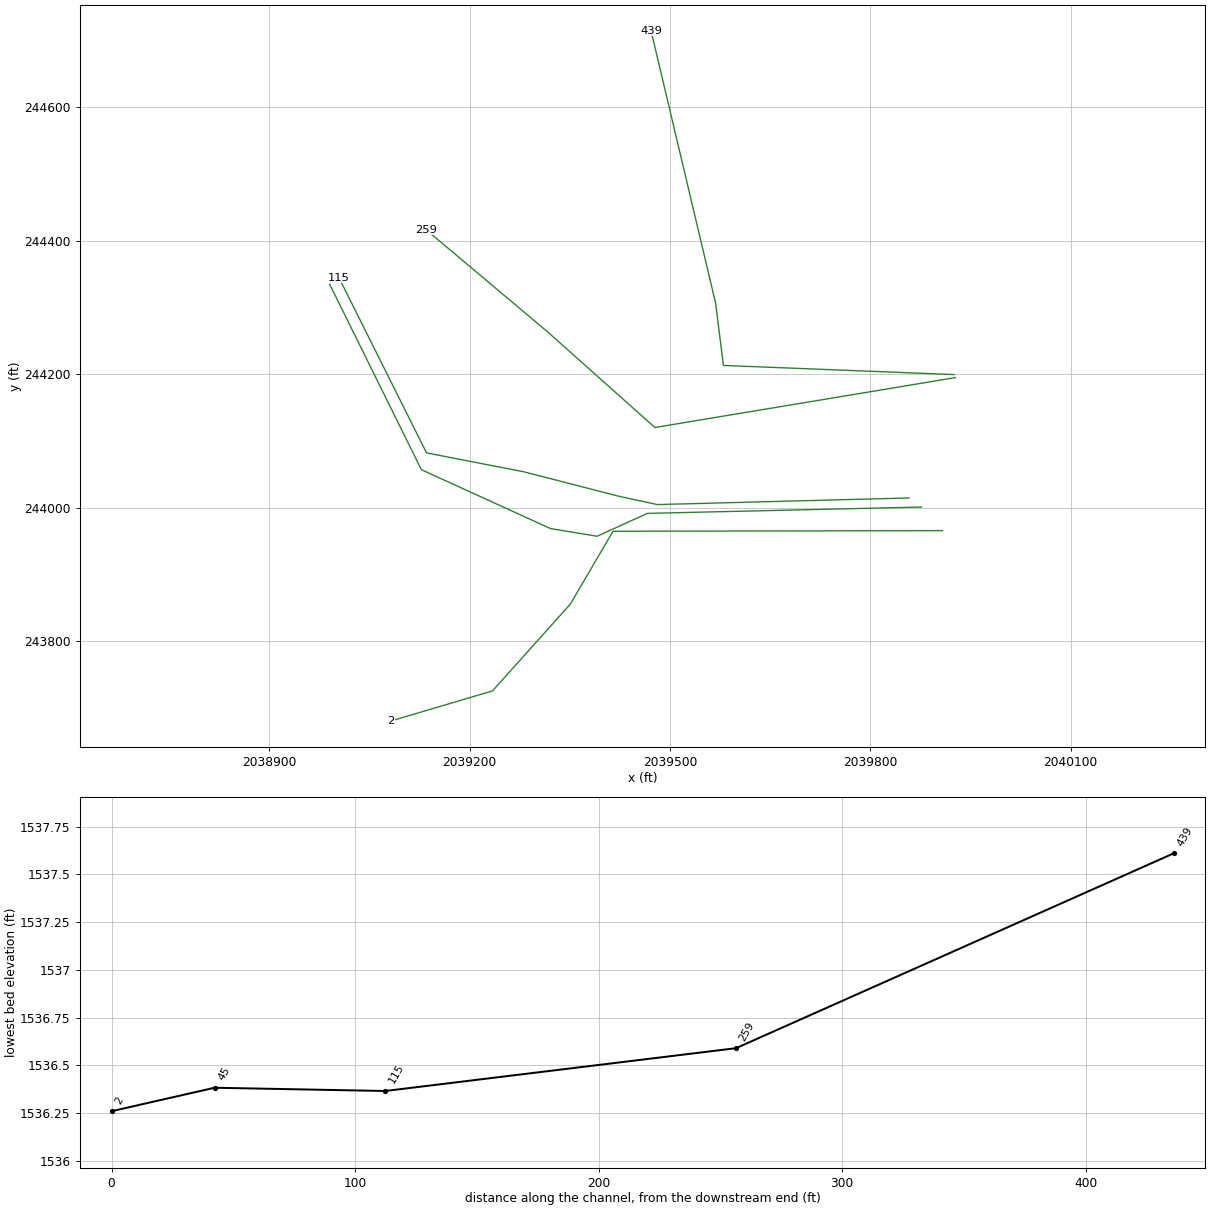
HEC-RAS study HNGRDCK_1.prj: HNGRDCK_1

--- HNGRDCK_1.g01 (geometry) --- (continued)

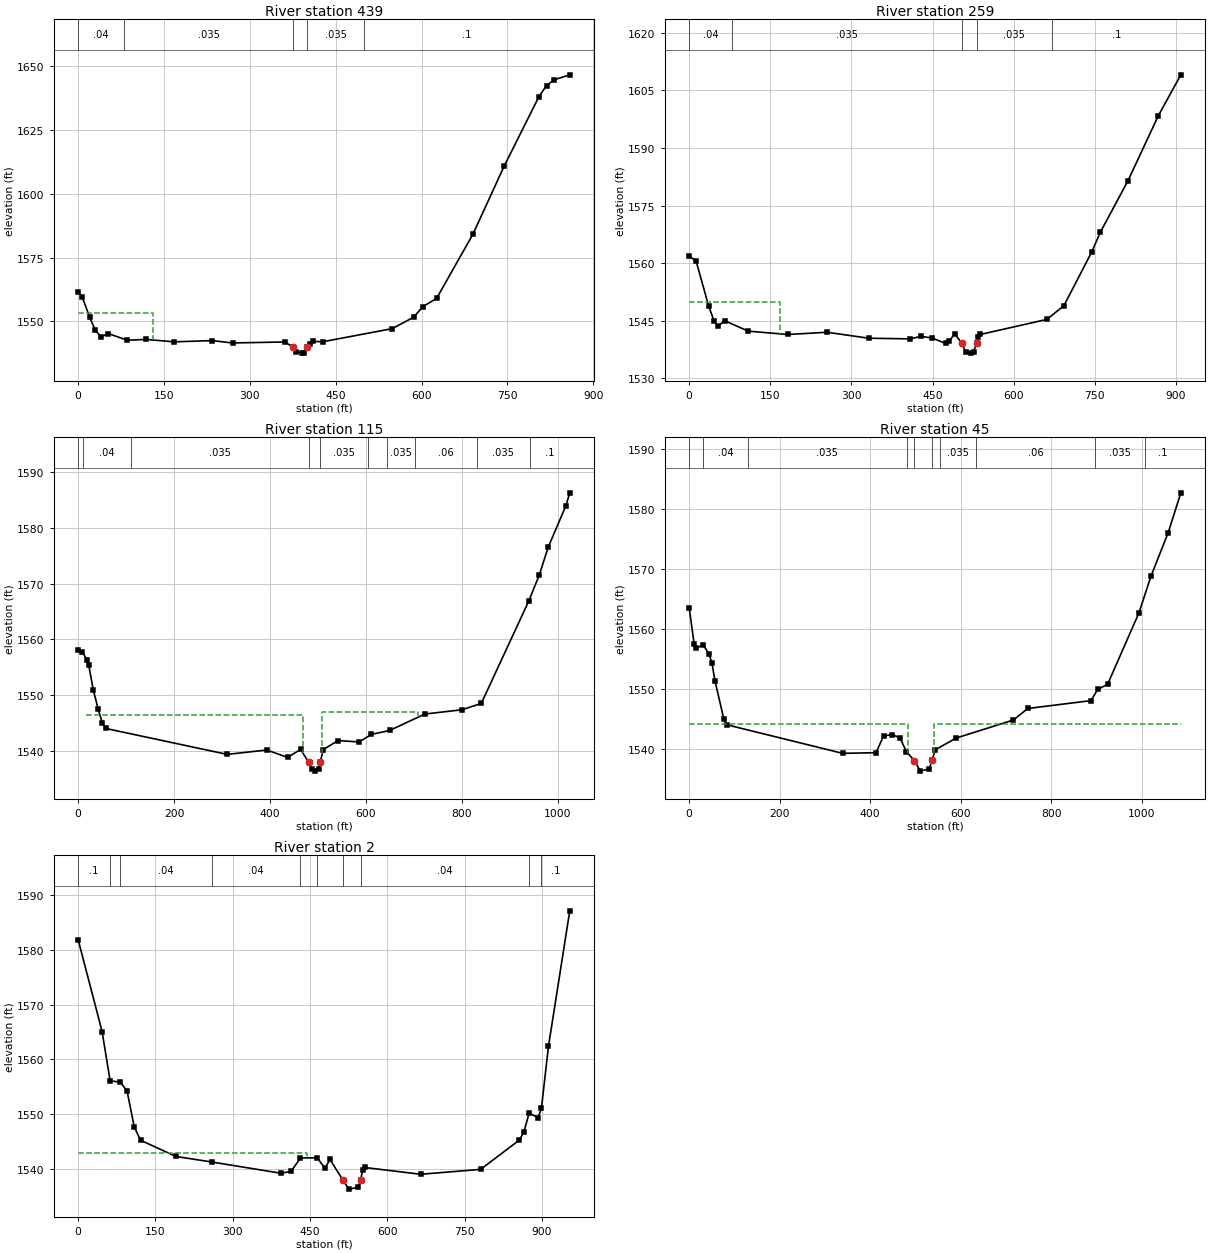
Type RM Length L Ch R = 1 ,439     ,161.9,179.7,194.2
XS GIS Cut Line= 4
2039925.13908466244199.2617605742039580.01837627244212.941779767
2039568.40101888244305.8806388742039471.58970731244714.424373702
#Sta/Elev= 30
       0 1561.59       7 1559.75    20.2 1551.61      30 1546.62    39.9    1544
      53 1545.25    85.8 1542.66   118.7 1542.97   167.9 1542.03   234.1 1542.52
   269.7 1541.59   361.3 1541.98   376.11539.847   381.2 1538.17   391.1 1537.61
   394.7 1537.81  400.441539.849   404.3  1541.3   410.9  1542.2   427.5 1542.07
   548.6 1547.19     586 1551.65   602.3 1555.81   626.2 1559.02   689.6  1584.1
   744.3 1610.81   804.9 1637.97   818.3 1642.34   831.8 1644.62858.9114 1646.55
#Mann= 5 ,-1 , 0
       0     .04       0      80    .035       0   376.1    .045       0
  400.44    .035       0  499.05      .1       0
#XS Ineff= 2 , 0
          130.37 1553.22
Permanent Ineff=
       F       F
Bank Sta=376.1,400.44
XS Rating Curve= 0 ,0
Exp/Cntr(USF)=0,0
Exp/Cntr=0.3,0.1

Type RM Length L Ch R = 1 ,259     ,133,144,155.5
XS GIS Cut Line= 4
2039927.45000272 244194.72343991  2039477.398386244120.002920659
2039316.69160879244263.2836617832039134.68634304244416.245534065
#Sta/Elev= 30
       0 1561.83    12.8 1560.57    36.1 1548.79    46.1 1544.93    52.7 1543.62
      66    1545   109.2 1542.31   182.4 1541.44   255.2 1542.02   331.9 1540.47
   408.6  1540.3   428.5 1540.94   449.1 1540.54   474.4  1539.1   481.4 1539.67
   490.7 1541.67  504.26 1539.16   511.6 1536.79   520.7 1536.59     526 1536.96
  531.491539.147   534.8  1540.8   538.3 1541.44   661.4 1545.36   692.9 1548.91
   744.1 1562.82   760.6  1568.1   811.5 1581.44   867.7 1598.38909.2629    1609
#Mann= 5 ,-1 , 0
       0     .04       0      80    .035       0  504.26    .045       0
  531.49    .035       0  671.52      .1       0
#XS Ineff= 2 , 0
          167.62 1549.92
Permanent Ineff=
       F       F
Bank Sta=504.26,531.49
XS Rating Curve= 0 ,0
Exp/Cntr(USF)=0,0
Exp/Cntr=0.5,0.3

Type RM Length L Ch R = 1 ,115     ,67.2,70.1,72
XS GIS Cut Line= 6
2039858.00569155244014.4919851852039481.09494159244004.602616873
2039423.43010715244017.0526295612039280.86770596244053.751861552
2039135.48228692244081.9820400062039004.21195711244344.522699627
#Sta/Elev= 30
       01558.045   8.8011557.711  18.6471556.333  21.9291555.415  31.7751550.891
  41.621 1547.53  50.5221545.001  58.0311544.014 310.7421539.369 393.1481540.152
 436.7891538.829 463.8911540.261  480.831537.914 486.5531536.775 494.3821536.366
 501.1571536.811 504.5451537.984 511.3211540.237 541.8111541.859 585.8171541.594
 611.5441542.962 649.3171543.656 722.8431546.611 800.2891547.375 840.4241548.515
 939.4621566.894 961.4711571.594 979.8111576.5181016.4921583.9151024.8751586.295
#Mann= 10 ,-1 , 0
       0      .1       0      10     .04       0     110    .035       0
  480.83    .045       0 504.545    .035       0  603.24     .06       0
  643.24    .035       0  703.24     .06       0  831.35    .035       0
  941.35      .1       0
#XS Ineff= 2 ,-1
   16.82  469.061546.443  509.12  708.811546.973
Permanent Ineff=
       F       F
Bank Sta=480.83,504.545
XS Rating Curve= 0 ,0
Exp/Cntr(USF)=0,0
Exp/Cntr=0.5,0.3

Type RM Length L Ch R = 1 ,45      ,10.7,42.3,73.5
XS GIS Cut Line= 6
2039876.63913377244000.9186972832039466.12692046243991.395539404
2039390.89661045243957.1495704572039321.06130448243968.658010391
 2039127.7089857244056.8544424792038990.38950813244334.531439164
#Sta/Elev= 30
       01563.584  11.0311557.549  14.3121556.813  30.7211557.407  43.8481555.908
  50.411 1554.32  56.9751551.408  76.6651545.026  83.2281544.099 339.2021539.344
 412.8241539.453   429.51542.239 447.5241542.468 465.5481541.956 479.9671539.628
 497.6261538.134 510.9261536.383 530.8761536.784 536.3661538.214 544.1771539.952
 589.9761541.891 716.4641544.898 748.0861546.813 887.8291548.123 903.0381550.024
  924.431550.826 993.9711562.7681020.2091568.8191058.4631576.0981086.3521582.726
#Mann= 10 ,-1 , 0
       0      .1       0      30     .04       0     130    .035       0
  480.62     .06       0 497.626    .045       0 536.366     .04       0
  553.28    .035       0  634.06     .06       0  896.58    .035       0
 1006.58      .1       0
#XS Ineff= 2 , 0
           484.5 1544.17  541.94         1544.29
Permanent Ineff=
       F       F
Bank Sta=497.626,536.366
XS Rating Curve= 0 ,0
Exp/Cntr(USF)=0,0
Exp/Cntr=0.5,0.3

Type RM Length L Ch R = 1 ,2       ,327.4,,197.9
XS GIS Cut Line= 6
2039908.00917245243965.5950568542039415.02198315 243964.61658924
2039412.59741889243961.1458892972039350.98622531243855.760894224
2039234.22641762243725.5804189892039081.26978616243680.259935588
#Sta/Elev= 30
       0 1581.91    46.5  1565.1    62.1 1556.08    81.8 1555.84    94.9 1554.23
   108.9 1547.65   121.1  1545.2     190 1542.23   258.9 1541.23   393.4 1539.17
   413.1 1539.52   431.3 1541.96     464 1541.99   478.7 1540.05   488.6  1541.7
 513.9341537.855   525.2 1536.26   543.7 1536.61 548.1021537.971   551.9 1539.75
   555.7 1540.22   664.5 1538.98   780.7 1539.87   855.4  1545.2   864.5 1546.64
   874.8 1550.16   892.3 1549.35   898.7 1551.04   912.4 1562.41   953.7 1587.18
#Mann= 10 ,-1 , 0
       0      .1       0    62.1    .013       0    81.8     .04       0
   258.9     .04       0   431.3    .013       0     464     .04       0
 513.934    .045       0 548.102     .04       0   874.8    .013       0
   898.7      .1       0
#XS Ineff= 2 , 0
          443.94 1542.89
Permanent Ineff=
       F       F
Bank Sta=513.934,548.102
XS Rating Curve= 0 ,0
Exp/Cntr(USF)=0,0
Exp/Cntr=0.3,0.1
LCMann Table=0

Chan Stop Cuts=-1
Use User Specified Reach Order=0
Composite Channel Slope=5